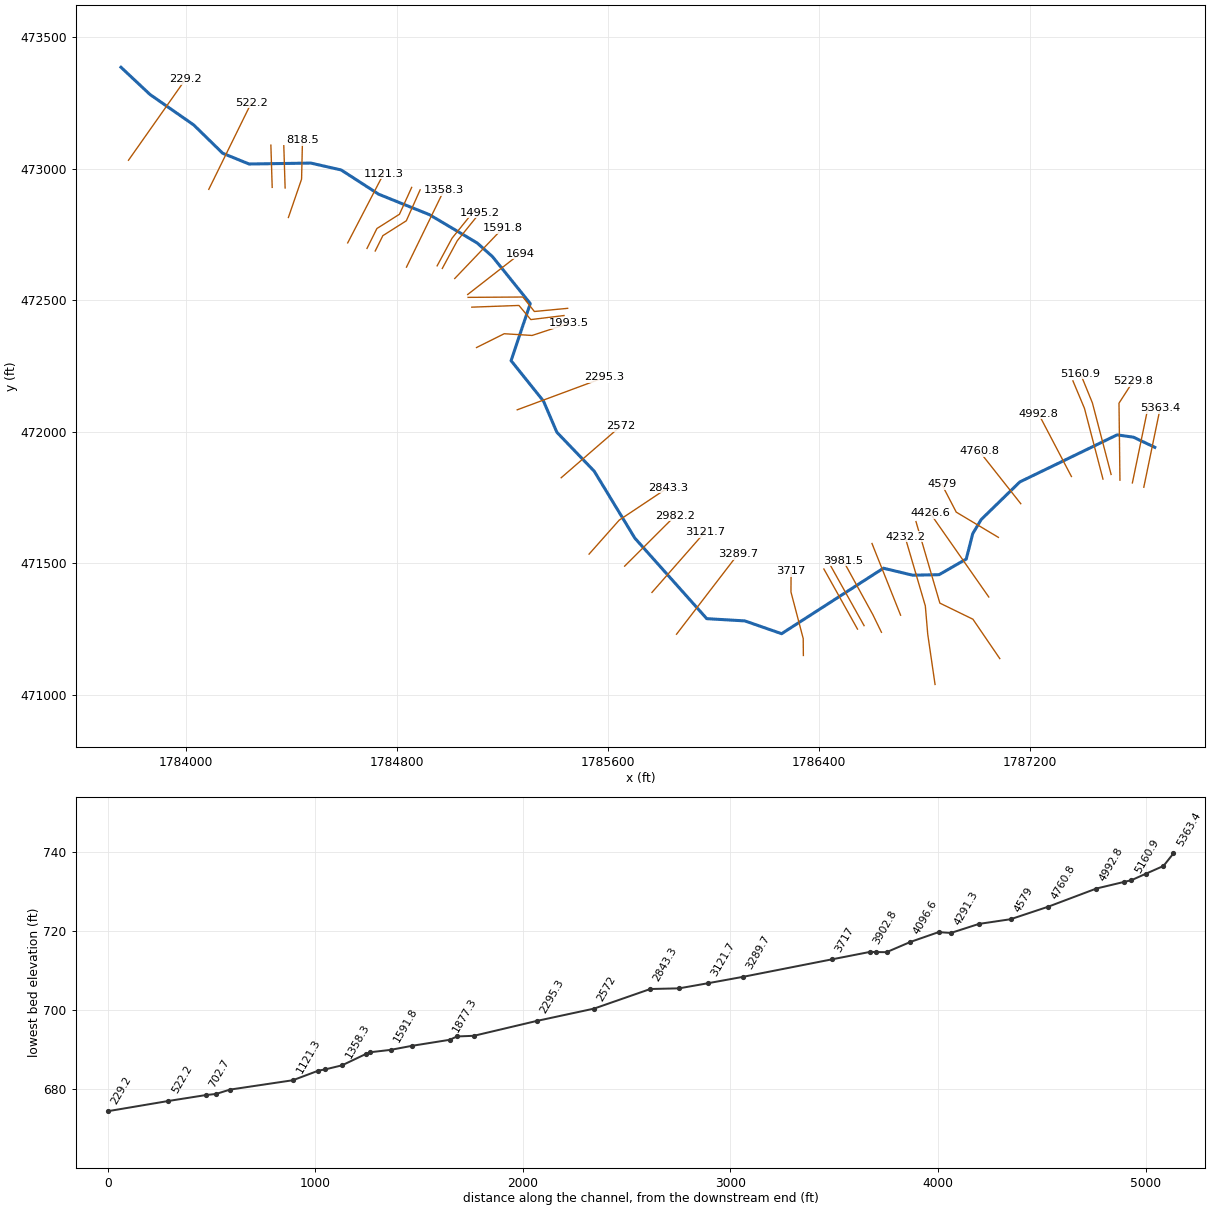
--- CANEFORK1.prj (project) ---

Proj Title=CANEFORK1
Current Plan=p01
Default Exp/Contr=0,0
English Units
Geom File=g01
Flow File=f01
Plan File=p01
BEGIN DESCRIPTION:
END DESCRIPTION:
DSS Export Rating Curves= 0
DSS Export Rating Curve Sorted= 0
DSS Export Volume Flow Curves= 0
DXF OffsetX= 0
DXF OffsetY= 0
DXF ScaleX= 0
DXF ScaleY= 0

--- CANEFORK1.p01 (plan) ---

Plan Title=Floodplain
Program Version=4.00
Geom File=g01
Flow File=f01
K Sum by GR=0
Std Step Tol=0.01
Critical Tol=0.01
Num of Std Step Trials=20
Max Error Tol=0.3
Flow Tol Ratio=0.001
Split Flow NTrial=30
Split Flow Tol=0.02
Split Flow Ratio=0.02
Log Output Level=0
Friction Slope Method=1
Unsteady Friction Slope Method=2
Unsteady Bridges Friction Slope Method=1
Global Log Level=0
CheckData=False
Run HTab=0
Run UNet=0
Run PostProcess=0
UNET Theta=0
UNET Theta Warmup=0
UNET ZTol=0
UNET ZSATol=0
UNET MxIter=0
UNET MaxInSteps=0
UNET DtIC=0
UNET DtMin=0
UNET MaxCRTS=0
UNET WFStab=0
UNET SFStab=0
UNET WFX=0
UNET SFX=0
UNET DSS MLevel=0
UNET DZMax Abort=0
UNET Convert EG Bridges=0
UNET Use Existing IB Tables=0
UNET Froude Limit=0
UNET Froude Power=0
Write IC File=0
Echo Input=False
Echo Output=False
Write Detailed=0

--- CANEFORK1.f01 (steady flow) ---

Flow Title=NFF Regression Equation
Program Version=4.10
Number of Profiles= 1
Profile Names=P100yr
River Rch & RM=CANEFORK1,Main            ,5363.4
772.5849
River Rch & RM=CANEFORK1,Main            ,4760.8
985.9076
River Rch & RM=CANEFORK1,Main            ,4579
 990.159
River Rch & RM=CANEFORK1,Main            ,4096.6
1436.341
River Rch & RM=CANEFORK1,Main            ,229.2
1490.225
Boundary for River Rch & Prof#=CANEFORK1,Main            , 1
Up Type= 0
Dn Type= 3
Dn Slope=0.0088
DSS Import GetInterval= 0
DSS Import GetPeak= 0
DSS Import FillOption= 0

--- CANEFORK1.g01 (geometry) ---

Geom Title=USGS 10m DEM
Program Version=4.10

River Reach=CANEFORK1       ,Main
Reach XY= 30
     1787675.477       471940.49     1787594.314      471979.073
      1787532.14       471987.85     1787163.055      471808.815
     1787016.515      471665.802     1786984.397      471611.982
     1786959.904      471515.659     1786856.792      471456.166
      1786756.26      471454.244      1786645.49      471480.826
     1786259.136      471231.774     1786119.813      471280.385
     1785975.153        471288.9     1785702.143      471595.261
     1785548.099      471849.687     1785406.432      471997.603
     1785355.559      472116.243     1785232.571      472270.085
     1785305.378        472487.2     1785161.988      472665.659
     1785103.654      472717.742     1784922.404      472825.381
     1784730.559      472902.701     1784587.802      472995.183
       1784472.7      473021.365     1784238.186      473017.842
     1784138.256      473058.654     1784028.215      473166.411
     1783862.235      473282.262     1783752.193        473385.7

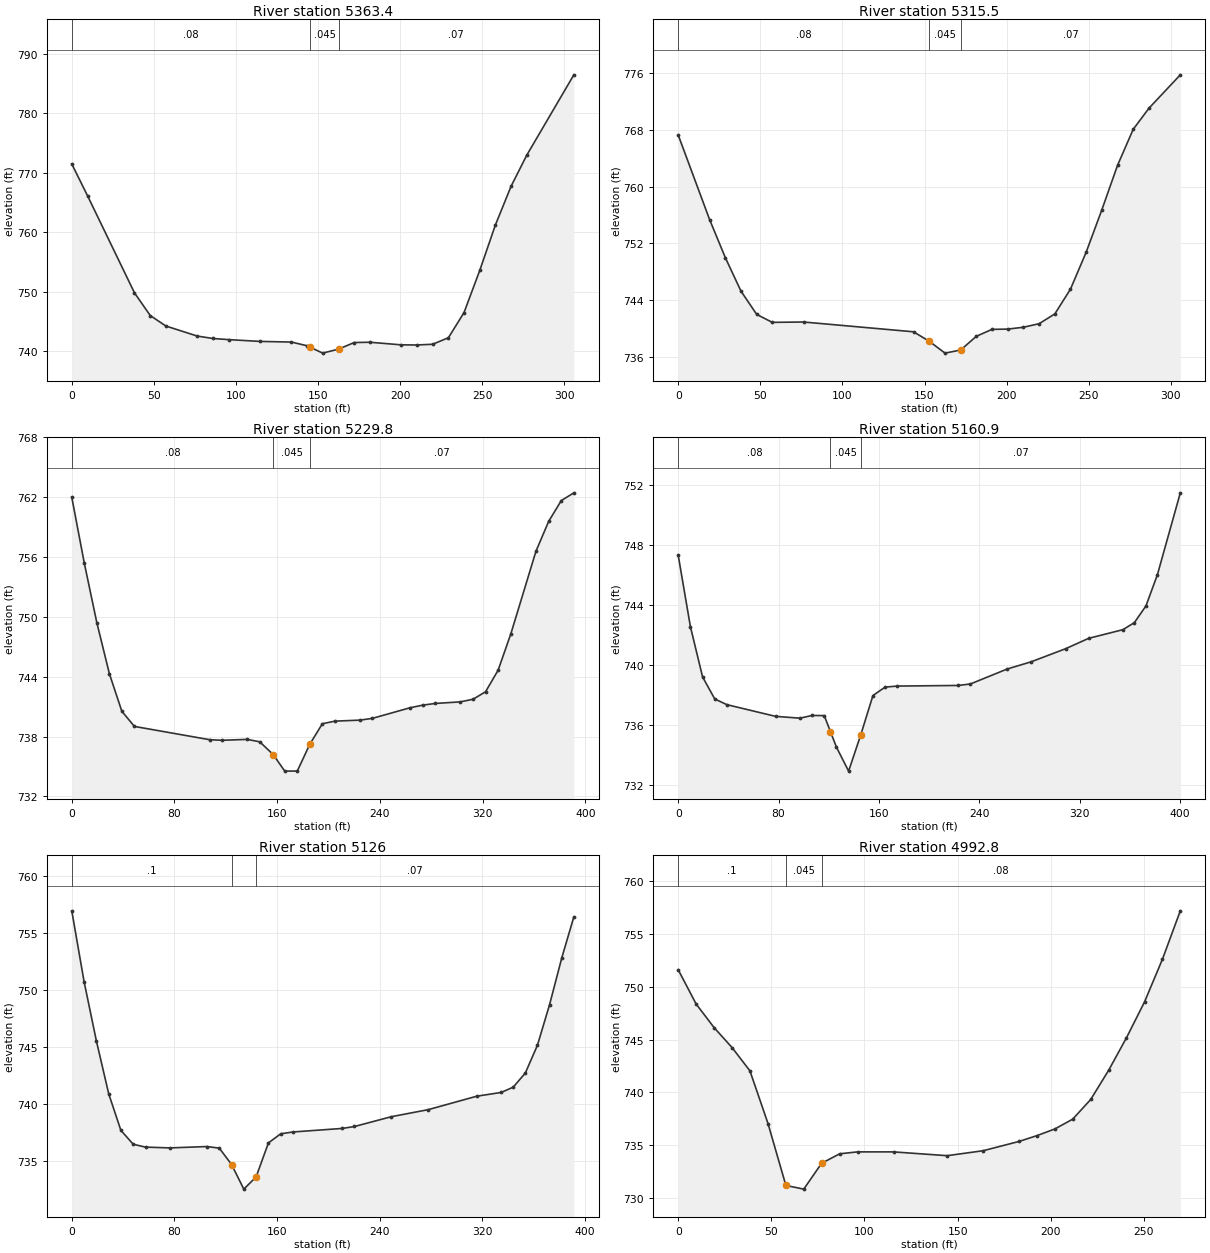
Type RM Length L Ch R = 1 ,5363.4  ,48,48,47.8
XS GIS Cut Line= 2
     1787633.658      471788.735     1787695.507      472088.214
#Sta/Elev= 26
       0  771.52     9.6  766.17    38.2  749.84    47.8  746.03    57.3  744.27
    76.4  742.58      86  742.17    95.6  741.98   114.7  741.68   133.8  741.57
   143.3  740.95   145.3 740.689   152.8  739.71   162.5  740.38     172  741.49
   181.6  741.54   200.7   741.1   210.2  741.08   219.8   741.2   229.4   742.3
   238.9  746.52   248.5  753.62     258  761.24   267.6  767.78   277.1  772.98
   305.8   786.5
#Mann= 3 , 0 , 0
       0     .08       0   145.3    .045       0   162.5     .07       0
Bank Sta=145.3,162.5
XS Rating Curve= 0 ,0
Exp/Cntr=0.3,0.1

Type RM Length L Ch R = 1 ,5315.5  ,80.8,85.7,90.4
XS GIS Cut Line= 2
     1787590.312      471805.154     1787652.161      472104.633
#Sta/Elev= 24
       0  767.29    19.1  755.37    28.7  749.99    38.2  745.28    47.8  741.99
    57.3  740.87    76.4  740.92   143.3  739.54   152.9   738.2   162.5  736.53
     172  736.97   181.6  738.91   191.1  739.88   200.7  739.92   210.2  740.18
   219.8  740.68   229.4  742.07   238.9  745.56   248.5  750.79     258  756.74
   267.6  763.04   277.1   768.1   286.7  771.08   305.8  775.79
#Mann= 3 , 0 , 0
       0     .08       0   152.9    .045       0     172     .07       0
Bank Sta=152.9,172
XS Rating Curve= 0 ,0
Exp/Cntr=0.3,0.1

Type RM Length L Ch R = 1 ,5229.8  ,63.4,68.9,74.4
XS GIS Cut Line= 3
     1787543.161      471815.647     1787539.517      472108.411
     1787592.834      472191.055
#Sta/Elev= 30
       0  761.99     9.8  755.36    19.5  749.43    29.3   744.3      39  740.54
    48.8  739.02   107.4  737.69   117.1  737.63   136.6  737.72   146.4  737.48
   156.9736.2011   165.9  734.54   175.7  734.55   185.4  737.23   195.2  739.29
     205  739.55   224.5  739.65   234.2  739.83   263.5  740.89   273.3  741.15
     283  741.32   302.6  741.48   312.5  741.74   322.3  742.49   332.1  744.65
     342  748.29   361.6  756.58   371.5  759.57   381.3  761.65   391.1  762.43
#Mann= 3 , 0 , 0
       0     .08       0   156.9    .045       0   185.4     .07       0
Bank Sta=156.9,185.4
XS Rating Curve= 0 ,0
Exp/Cntr=0.3,0.1

Type RM Length L Ch R = 1 ,5160.9  ,35,35,35
XS GIS Cut Line= 3
     1787509.603      471837.363     1787438.526      472109.614
     1787393.701      472219.629
#Sta/Elev= 27
       0   747.3     9.7  742.55    19.4   739.2    29.1  737.73    38.8  737.35
    77.6  736.57      97  736.45   106.7  736.63   116.4  736.62   121.3735.5592
   126.1  734.52   135.8  732.92   145.5  735.34   155.2  737.96   164.9  738.52
   174.6  738.59   223.2  738.63   232.9  738.73     262  739.72   281.4  740.21
   308.8  741.08   327.1  741.77   354.5  742.35   363.6  742.82   372.8  743.93
   381.9     746   400.2  751.47
#Mann= 3 , 0 , 0
       0     .08       0   121.3    .045       0   145.5     .07       0
Bank Sta=121.3,145.5
XS Rating Curve= 0 ,0
Exp/Cntr=0.3,0.1

Type RM Length L Ch R = 1 ,5126    ,127.9,133.2,138.2
XS GIS Cut Line= 3
     1787478.736      471819.631     1787408.544       472088.49
     1787364.688      472193.253
#Sta/Elev= 28
       0  756.93     9.6  750.71    19.2   745.5    28.8  740.86    38.3  737.65
    47.9  736.43    57.5  736.18    76.6  736.11   105.4  736.23     115  736.09
   124.6  734.65   134.1  732.49   143.7  733.56   153.3  736.55   162.9  737.35
   172.5  737.51   210.8  737.82   220.4  737.99   249.1  738.85   277.9  739.47
   315.7  740.65   334.7  740.98   344.1  741.44   353.6  742.69     363  745.12
   372.5   748.7     382   752.8   391.4   756.4
#Mann= 3 , 0 , 0
       0      .1       0   124.6    .045       0   143.7     .07       0
Bank Sta=124.6,143.7
XS Rating Curve= 0 ,0
Exp/Cntr=0.3,0.1

Type RM Length L Ch R = 1 ,4992.8  ,227.7,232,236.1
XS GIS Cut Line= 2
     1787358.925      471829.612     1787233.925      472068.501
#Sta/Elev= 24
       0  751.61     9.6  748.37    19.3  746.12    28.9  744.24    38.5  742.03
    48.2  737.04    57.8  731.17    67.4  730.82      77  733.27    86.7  734.17
    96.3  734.35   115.6  734.35   144.4  733.99   163.7  734.46     183  735.34
   192.6  735.89   202.2  736.52   211.8  737.45   221.5  739.32   231.1  742.08
   240.7  745.17   250.4  748.57     260  752.61   269.6   757.2
#Mann= 3 , 0 , 0
       0      .1       0    57.8    .045       0      77     .08       0
Bank Sta=57.8,77
XS Rating Curve= 0 ,0
Exp/Cntr=0.3,0.1

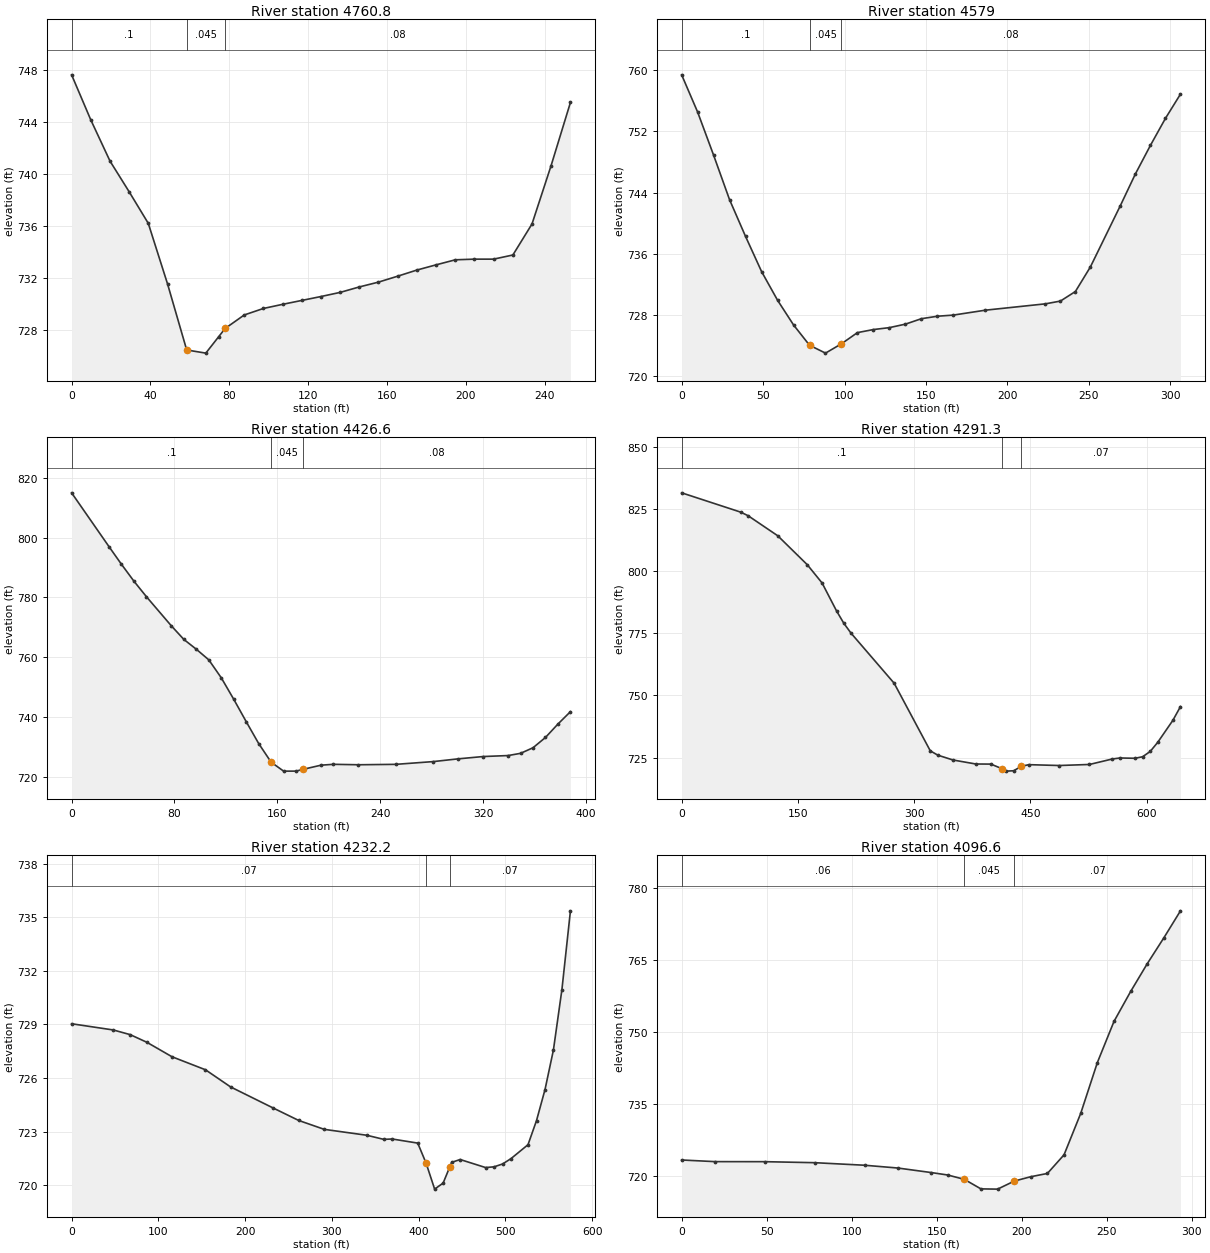
Type RM Length L Ch R = 1 ,4760.8  ,173.3,181.7,189.6
XS GIS Cut Line= 2
     1787166.737      471726.159      1787010.02      471924.848
#Sta/Elev= 29
       0  747.66     9.7   744.2    19.5  741.01    29.2  738.65    38.9  736.22
    48.7  731.54    58.4  726.46    59.7  726.43    68.1  726.22    74.7   727.5
    77.9  728.12    87.6  729.16    97.3  729.66   107.1  729.98   116.8  730.28
   126.5  730.58   136.3   730.9     146  731.32   155.7  731.69   165.5  732.15
   175.2  732.62   184.9  733.02   194.7  733.41   204.4  733.46   214.1  733.46
   223.9  733.78   233.6  736.17   243.3  740.67   253.1  745.53
#Mann= 3 , 0 , 0
       0      .1       0    58.4    .045       0    77.9     .08       0
Bank Sta=58.4,77.9
XS Rating Curve= 0 ,0
Exp/Cntr=0.3,0.1

Type RM Length L Ch R = 1 ,4579    ,161.9,152.4,142.8
XS GIS Cut Line= 3
     1787081.807      471598.087      1786921.96      471693.995
     1786866.833      471800.322
#Sta/Elev= 28
       0   759.4     9.8  754.54    19.6  748.91    29.4  743.09    39.2   738.3
    49.1  733.68    58.9  729.94    68.7  726.72    78.5  724.07    88.3  723.04
    98.1  724.26   107.9  725.72   117.7  726.12   127.5  726.37   137.4  726.83
   147.2  727.54     157  727.86   166.8  728.01   186.4  728.65   223.3  729.48
   232.5  729.84   241.7  731.09   250.9   734.3   269.3  742.31   278.5  746.44
   287.8   750.2     297  753.72   306.2  756.88
#Mann= 3 , 0 , 0
       0      .1       0    78.5    .045       0    98.1     .08       0
Bank Sta=78.5,98.1
XS Rating Curve= 0 ,0
Exp/Cntr=0.3,0.1

Type RM Length L Ch R = 1 ,4426.6  ,142.6,135.3,128
XS GIS Cut Line= 2
     1787045.399      471371.293      1786823.32      471689.435
#Sta/Elev= 30
       0  814.95    29.1  796.94    38.8  791.03    48.5  785.38    58.2   780.2
    77.6  770.44    87.3  765.91      97  762.63   106.7  759.08   116.4  753.08
   126.1   745.9   135.8  738.41   145.5  731.09   155.2  724.84   164.9  721.85
   174.6  721.85   180.3722.4788     194  723.84   203.7  724.13   223.1  723.98
   252.2  724.12   281.3  725.04   300.7  725.96   320.1  726.73   339.5  727.06
   349.2   727.8   358.9  729.67   368.6  733.12   378.3  737.61     388  741.74
#Mann= 3 , 0 , 0
       0      .1       0   155.2    .045       0   180.3     .08       0
Bank Sta=155.2,180.3
XS Rating Curve= 0 ,0
Exp/Cntr=0.3,0.1

Type RM Length L Ch R = 1 ,4291.3  ,59,59.2,59.7
XS GIS Cut Line= 4
     1787087.126      471137.078     1786985.171       471286.82
       1786859.7      471348.083     1786769.175      471657.981
#Sta/Elev= 30
       0  831.54    76.3  823.76    85.8  822.32     124  814.26   162.1  802.61
   181.2  795.26   199.8  784.06   209.1  779.12   218.4  775.13   274.2  754.92
   320.8  727.72   330.6  725.97   350.1  724.04   379.5  722.43     399  722.39
   412.8720.6076   418.6  719.56   428.4  719.71   438.2  721.49     448  722.16
   487.1  721.82   526.2  722.24   555.6  724.44   565.4  724.85   584.9  724.73
   594.7  725.34   604.5  727.46   614.3  731.17   633.8     740   643.6  745.54
#Mann= 3 , 0 , 0
       0      .1       0   412.8    .045       0   438.2     .07       0
Bank Sta=412.8,438.2
XS Rating Curve= 0 ,0
Exp/Cntr=0.3,0.1

Type RM Length L Ch R = 1 ,4232.2  ,133.2,135.5,137.2
XS GIS Cut Line= 4
     1786841.467      471038.814     1786813.747      471229.702
     1786804.549      471337.487     1786727.575      471600.276
#Sta/Elev= 30
       0  729.04    48.2  728.69    67.5  728.43    86.8     728   115.7  727.19
   154.3  726.46   183.2   725.5   232.2  724.32   261.7  723.62   291.2  723.12
   340.2  722.79   359.7  722.56   369.5  722.58   398.9  722.35   408.6  721.22
   418.4  719.77   428.2  720.11     436721.0342     438  721.27   447.8  721.43
   477.1  720.98   486.9  721.02   496.7  721.18   506.4  721.48     526  722.26
   535.8  723.61   545.6  725.35   555.3  727.57   565.1  730.96   574.9  735.37
#Mann= 3 , 0 , 0
       0     .07       0   408.6    .045       0     436     .07       0
Bank Sta=408.6,436
XS Rating Curve= 0 ,0
Exp/Cntr=0.3,0.1

Type RM Length L Ch R = 1 ,4096.6  ,112.2,115.2,117.8
XS GIS Cut Line= 2
       1786710.7       471302.12     1786602.184      471574.821
#Sta/Elev= 22
       0  723.35    19.6  723.01    48.9     723    78.3  722.79   107.6  722.26
   127.2  721.68   146.8  720.74   156.5  720.23   166.3  719.33   176.1  717.34
   185.9  717.29   195.7  718.96   205.4  719.87   215.2  720.55     225  724.43
   234.8  733.04   244.6  743.62   254.4  752.19   264.2  758.41   273.9  764.15
   283.7  769.55   293.5  775.18
#Mann= 3 , 0 , 0
       0     .06       0   166.3    .045       0   195.7     .07       0
Bank Sta=166.3,195.7
XS Rating Curve= 0 ,0
Exp/Cntr=0.3,0.1

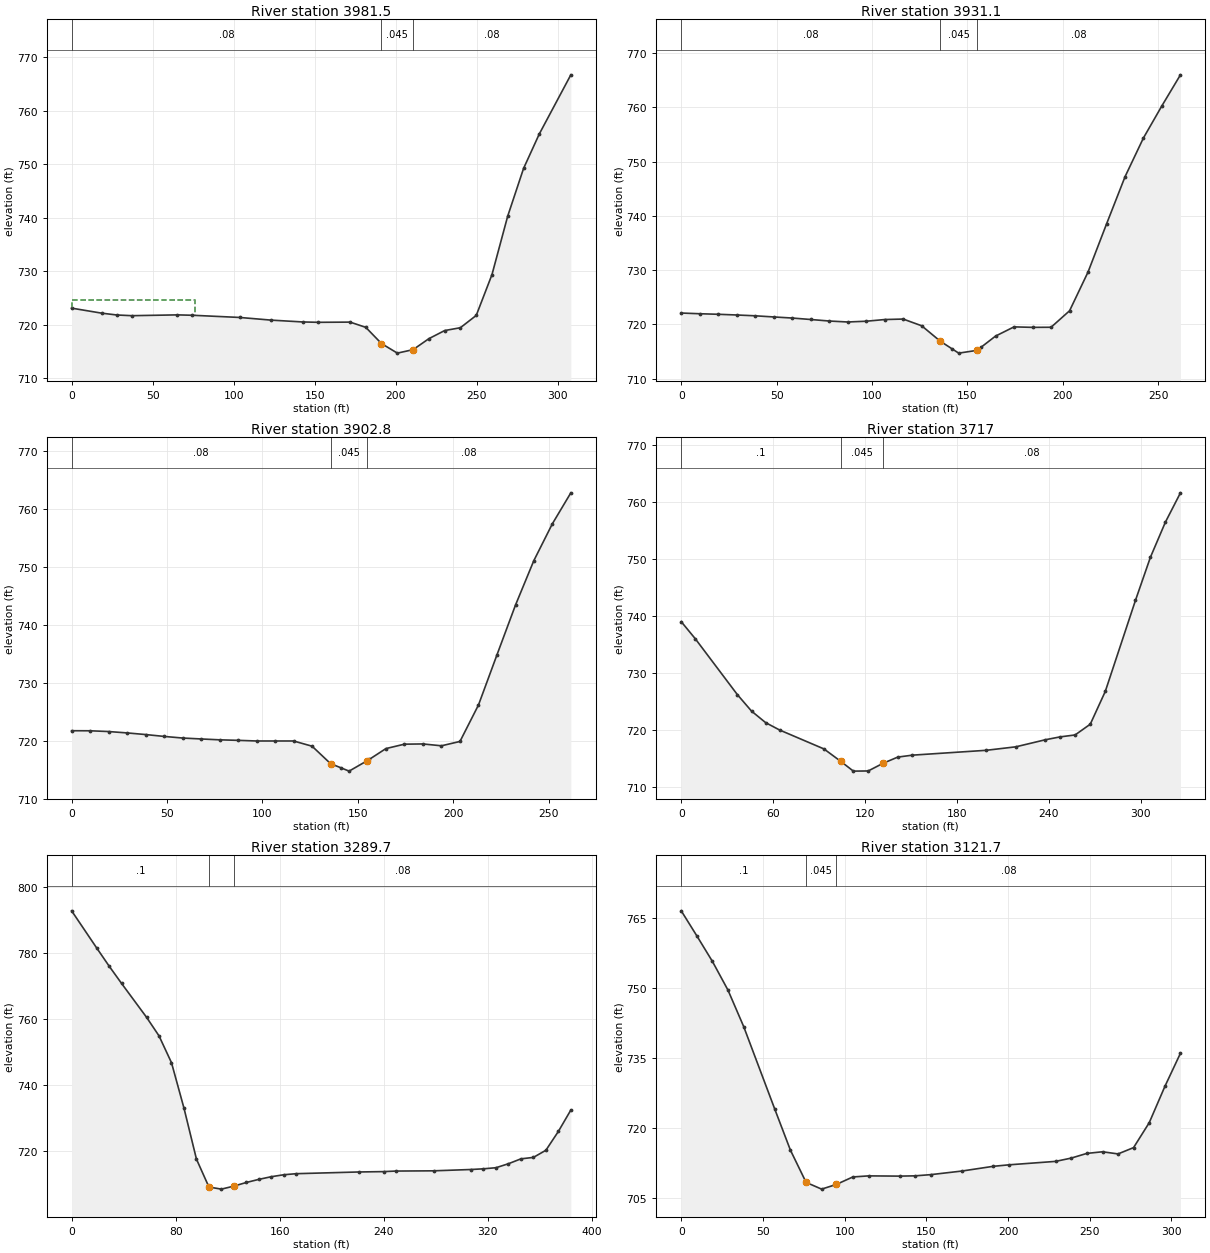
Type RM Length L Ch R = 1 ,3981.5  ,50.2,50.4,50.6
XS GIS Cut Line= 3
     1786638.033      471237.103     1786605.466      471304.097
     1786493.222      471509.084
#Sta/Elev= 24
       0   723.1    18.6  722.16    27.9  721.82    37.2  721.69    65.2  721.84
    74.5  721.77   103.7  721.36   123.2  720.86   142.6  720.52   152.4  720.45
   171.9  720.49   181.6  719.51   191.3  716.48   201.1  714.69   210.8  715.34
   220.6   717.4   230.3  718.91     240  719.44   249.8  721.74   259.5  729.36
   269.2  740.28     279  749.21   288.7  755.65   308.2  766.72
#Mann= 3 , 0 , 0
       0     .08       0   191.3    .045       0   210.8     .08       0
#XS Ineff= 2 , 0
           76.36  724.62
Permanent Ineff=
       F       F
Bank Sta=191.3,210.8
XS Rating Curve= 0 ,0
Exp/Cntr=0.3,0.1

Type RM Length L Ch R = 1 ,3931.1  ,28.3,28.3,28.3
XS GIS Cut Line= 2
     1786572.157      471262.474     1786444.685      471490.944
#Sta/Elev= 30
       0  722.11     9.7  721.98    19.4  721.88    29.1  721.75    38.8   721.6
    48.4  721.39    58.1  721.19    67.8  720.92    77.5  720.64    87.2  720.46
    96.9   720.6   106.6  720.91   116.3     721     126  719.76   135.7  716.93
     142  715.49   145.4  714.72     155  715.23     157  715.77   164.7  717.86
   174.4  719.56   184.1  719.47   193.8  719.49   203.5  722.53   213.2  729.69
   222.9  738.56   232.6  747.27   242.2  754.38   251.9  760.32   261.6  766.02
#Mann= 3 , 0 , 0
       0     .08       0   135.7    .045       0     155     .08       0
Bank Sta=135.7,155
XS Rating Curve= 0 ,0
Exp/Cntr=0.3,0.1

Type RM Length L Ch R = 1 ,3902.8  ,191.1,185.8,179.4
XS GIS Cut Line= 2
     1786547.153      471249.237     1786419.681      471477.706
#Sta/Elev= 30
       0  721.74     9.7  721.73    19.4   721.6    29.1  721.36    38.8  721.08
    48.4  720.76    58.1  720.48    67.8  720.32    77.5  720.17    87.2  720.08
    96.9  719.97   106.6  719.97   116.3  719.97     126  719.07   135.7  716.06
     141  715.36   145.4  714.77     155  716.59     156   716.8   164.7  718.66
   174.4  719.42   184.1  719.46   193.8  719.14   203.5  719.89   213.2  726.18
   222.9  734.84   232.6  743.42   242.2  751.08   251.9  757.43   261.6  762.78
#Mann= 3 , 0 , 0
       0     .08       0   135.7    .045       0     155     .08       0
Bank Sta=135.7,155
XS Rating Curve= 0 ,0
Exp/Cntr=0.3,0.1

Type RM Length L Ch R = 1 ,3717    ,447.9,427.3,407
XS GIS Cut Line= 4
     1786341.727      471149.045     1786341.173      471213.275
     1786294.661      471390.462     1786295.215      471469.088
#Sta/Elev= 24
       0  739.05     9.2  736.05    36.7  726.25    45.9  723.38    55.1  721.36
    64.2  720.07    93.2  716.75   104.2 714.569   112.4  712.86   122.1  712.89
   131.7  714.22   141.4  715.32     151  715.66   199.2  716.51   218.5  717.12
   237.8  718.36   247.4  718.86   257.2   719.2   267.1  721.08   276.9  726.82
   296.6  742.77   306.4  750.35   316.2  756.51     326  761.63
#Mann= 3 , 0 , 0
       0      .1       0   104.2    .045       0   131.7     .08       0
Bank Sta=104.2,131.7
XS Rating Curve= 0 ,0
Exp/Cntr=0.3,0.1

Type RM Length L Ch R = 1 ,3289.7  ,169.6,168.1,166.6
XS GIS Cut Line= 2
     1785860.414      471229.788     1786093.921      471534.475
#Sta/Elev= 30
       0  792.82    19.2   781.6    28.8  776.08    38.4  770.81    57.6  760.55
    67.2  754.91    76.8  746.77    86.4  732.99      96  717.53   105.6  709.07
   115.2  708.44   124.8  709.36   134.4  710.46     144   711.4   153.6  712.21
   163.2   712.8   172.7  713.12   220.7  713.64   239.9  713.75   249.5  713.92
   278.3  713.99   307.1  714.39   316.7   714.6   326.3  714.93   335.9  716.14
   345.5  717.62   355.1  718.06   364.7  720.22   374.3  725.93   383.9  732.42
#Mann= 3 , 0 , 0
       0      .1       0   105.6    .045       0   124.8     .08       0
Bank Sta=105.6,124.8
XS Rating Curve= 0 ,0
Exp/Cntr=0.3,0.1

Type RM Length L Ch R = 1 ,3121.7  ,140.9,139.4,137.9
XS GIS Cut Line= 2
      1785767.15      471388.719      1785968.47      471618.496
#Sta/Elev= 27
       0  766.51     9.6  761.11    19.1  755.65    28.6  749.51    38.2   741.7
    57.3  723.93    66.8   715.2    76.4  708.28    85.9  706.83    94.9707.8334
     105  709.44   114.6  709.67   133.6  709.62   143.2  709.68   152.8  709.94
   171.8  710.71   190.9  711.72   200.5  712.04   229.1  712.78   238.7  713.49
   248.2  714.49   257.8  714.84   267.3  714.38   276.8  715.73   286.4  721.08
     296  728.88   305.5  735.97
#Mann= 3 , 0 , 0
       0      .1       0    76.4    .045       0    94.9     .08       0
Bank Sta=76.4,94.9
XS Rating Curve= 0 ,0
Exp/Cntr=0.3,0.1

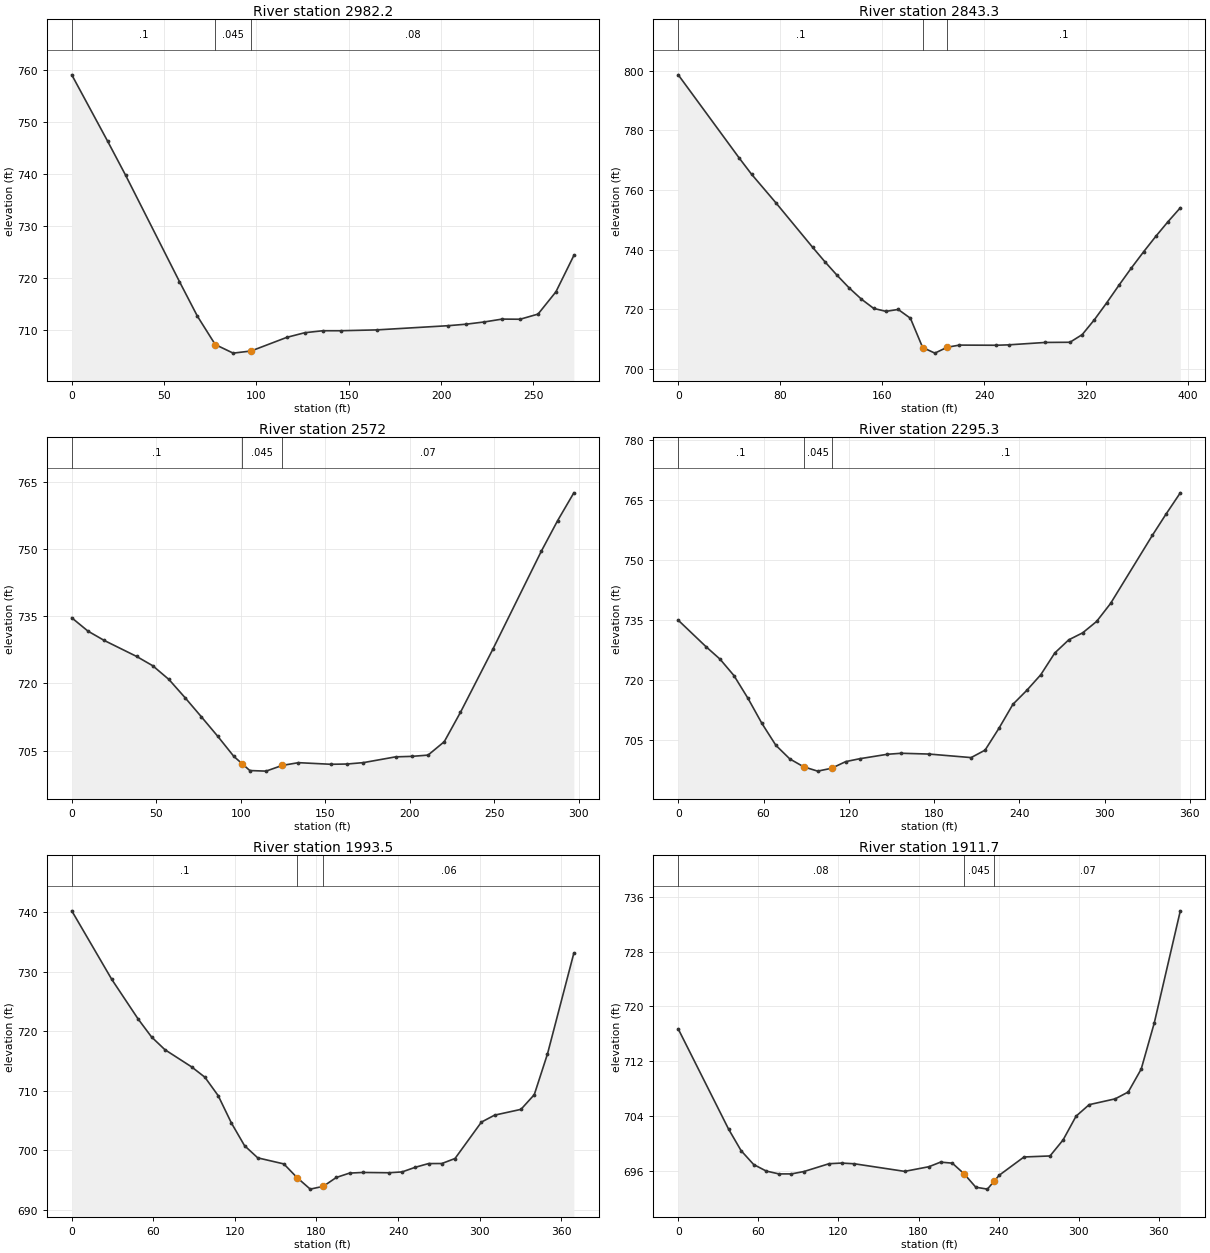
Type RM Length L Ch R = 1 ,2982.2  ,142.9,138.9,134.5
XS GIS Cut Line= 2
     1785663.558      471488.637     1785855.889      471680.852
#Sta/Elev= 21
       0  759.08    19.4  746.32    29.1   739.8    58.3  719.31      68  712.66
    77.7  707.18    87.4  705.53    97.1  705.94   116.5  708.57   126.2  709.46
     136  709.84   145.7  709.84   165.1     710   203.9  710.81   213.6   711.1
   223.4  711.53   233.1  712.08   242.8  712.05   252.5  713.04   262.2  717.33
   271.9  724.32
#Mann= 3 , 0 , 0
       0      .1       0    77.7    .045       0    97.1     .08       0
Bank Sta=77.7,97.1
XS Rating Curve= 0 ,0
Exp/Cntr=0.3,0.1

Type RM Length L Ch R = 1 ,2843.3  ,268.9,271.3,274.1
XS GIS Cut Line= 3
     1785528.546       471534.45     1785642.941      471663.635
     1785827.145       471786.61
#Sta/Elev= 30
       0  798.56    47.9  770.67    57.5  765.29    76.7  755.67   105.4  740.83
     115  736.01   124.6  731.45   134.2  727.17   143.8  723.42   153.4  720.33
     163  719.35   172.6  719.99   182.2  717.04   191.8  707.24   201.4  705.36
   211.1  707.34   220.7  708.05   249.6     708   259.2  708.13   288.1  708.94
   307.4     709     317  711.56   326.6  716.56   336.3  722.25   345.9  728.13
   355.5  733.82   365.2   739.3   374.8  744.49   384.4  749.41     394  754.03
#Mann= 3 , 0 , 0
       0      .1       0   191.8    .045       0   211.1      .1       0
Bank Sta=191.8,211.1
XS Rating Curve= 0 ,0
Exp/Cntr=0.3,0.1

Type RM Length L Ch R = 1 ,2572    ,284.9,276.7,268.5
XS GIS Cut Line= 2
     1785422.699      471824.804     1785647.018      472019.748
#Sta/Elev= 27
       0  734.66     9.6  731.68    19.2   729.6    38.4  726.02    47.9  723.95
    57.5  720.88    67.1  716.79    76.7  712.54    86.3  708.23    95.9   703.7
   100.9702.0263   105.4  700.52     115  700.39   124.6  701.67   134.2  702.28
   153.4  701.92     163  701.98   172.6  702.29   191.7  703.58   201.3  703.69
   210.9  703.97   220.5  706.97   230.1  713.55   249.3  727.67     278  749.58
   287.6  756.38   297.2  762.59
#Mann= 3 , 0 , 0
       0      .1       0   100.9    .045       0   124.6     .07       0
Bank Sta=100.9,124.6
XS Rating Curve= 0 ,0
Exp/Cntr=0.3,0.1

Type RM Length L Ch R = 1 ,2295.3  ,311.2,301.7,290.8
XS GIS Cut Line= 2
     1785255.895      472083.124     1785586.971       472206.34
#Sta/Elev= 30
       0  734.94    19.6  728.31    29.4  725.22    39.2  721.12    49.1  715.42
    58.9  709.16    68.7  703.71    78.5  700.31    88.3  698.33    98.1  697.26
   107.9  697.97   117.8  699.63   127.6  700.35   147.2  701.47     157  701.72
   176.6  701.52   206.1  700.64   215.9   702.5   225.7  707.97   235.5  713.94
   245.3  717.44   255.1  721.32     265  726.77   274.8  730.04   284.6  731.79
   294.4  734.63   304.2  739.11   333.6  756.11   343.4  761.51   353.3  766.74
#Mann= 3 , 0 , 0
       0      .1       0    88.3    .045       0   107.9      .1       0
Bank Sta=88.3,107.9
XS Rating Curve= 0 ,0
Exp/Cntr=0.3,0.1

Type RM Length L Ch R = 1 ,1993.5  ,101.2,81.8,61.5
XS GIS Cut Line= 4
     1785101.463      472319.902       1785206.5      472372.451
     1785312.446      472365.908     1785450.819      472411.551
#Sta/Elev= 30
       0  740.23    29.4  728.73    48.9  722.04    58.7  719.05    68.5  716.92
    88.1  714.04    97.9   712.3   107.7   709.2   117.4  704.62   127.1   700.8
   136.8  698.76     156  697.74   165.7  695.45   175.4  693.51     185  693.98
   194.6  695.47   204.3   696.2     214  696.31   233.3  696.26     243   696.4
   252.7  697.18   262.4   697.8   272.2  697.81   281.9  698.65   301.3  704.76
     311  705.93   330.4   706.9   340.2  709.37   349.9   716.2   369.3  733.13
#Mann= 3 , 0 , 0
       0      .1       0   165.7    .045       0     185     .06       0
Bank Sta=165.7,185
XS Rating Curve= 0 ,0
Exp/Cntr=0.3,0.1

Type RM Length L Ch R = 1 ,1911.7  ,55.5,34.4,35.3
XS GIS Cut Line= 4
     1785083.463      472473.496     1785262.317      472480.001
     1785307.456      472426.182     1785433.416      472441.638
#Sta/Elev= 30
       0  716.71    37.7   702.1    47.1  698.95    56.5  696.93    65.9  695.98
    75.4  695.56    84.8  695.56    94.2  695.91     113  697.05   122.4  697.14
   131.9  697.04   169.6  695.93   187.8  696.61   196.5  697.28   205.3  697.13
   214.1  695.58   222.9  693.62   231.6  693.34   236.9694.5566   240.4  695.36
     259  698.03   278.5  698.18   288.3  700.52     298  703.98   307.8  705.66
   327.3  706.51   337.1  707.51   346.8  710.85   356.6  717.59   376.1  733.94
#Mann= 3 , 0 , 0
       0     .08       0   214.1    .045       0   236.9     .07       0
Bank Sta=214.1,236.9
XS Rating Curve= 0 ,0
Exp/Cntr=0.3,0.1

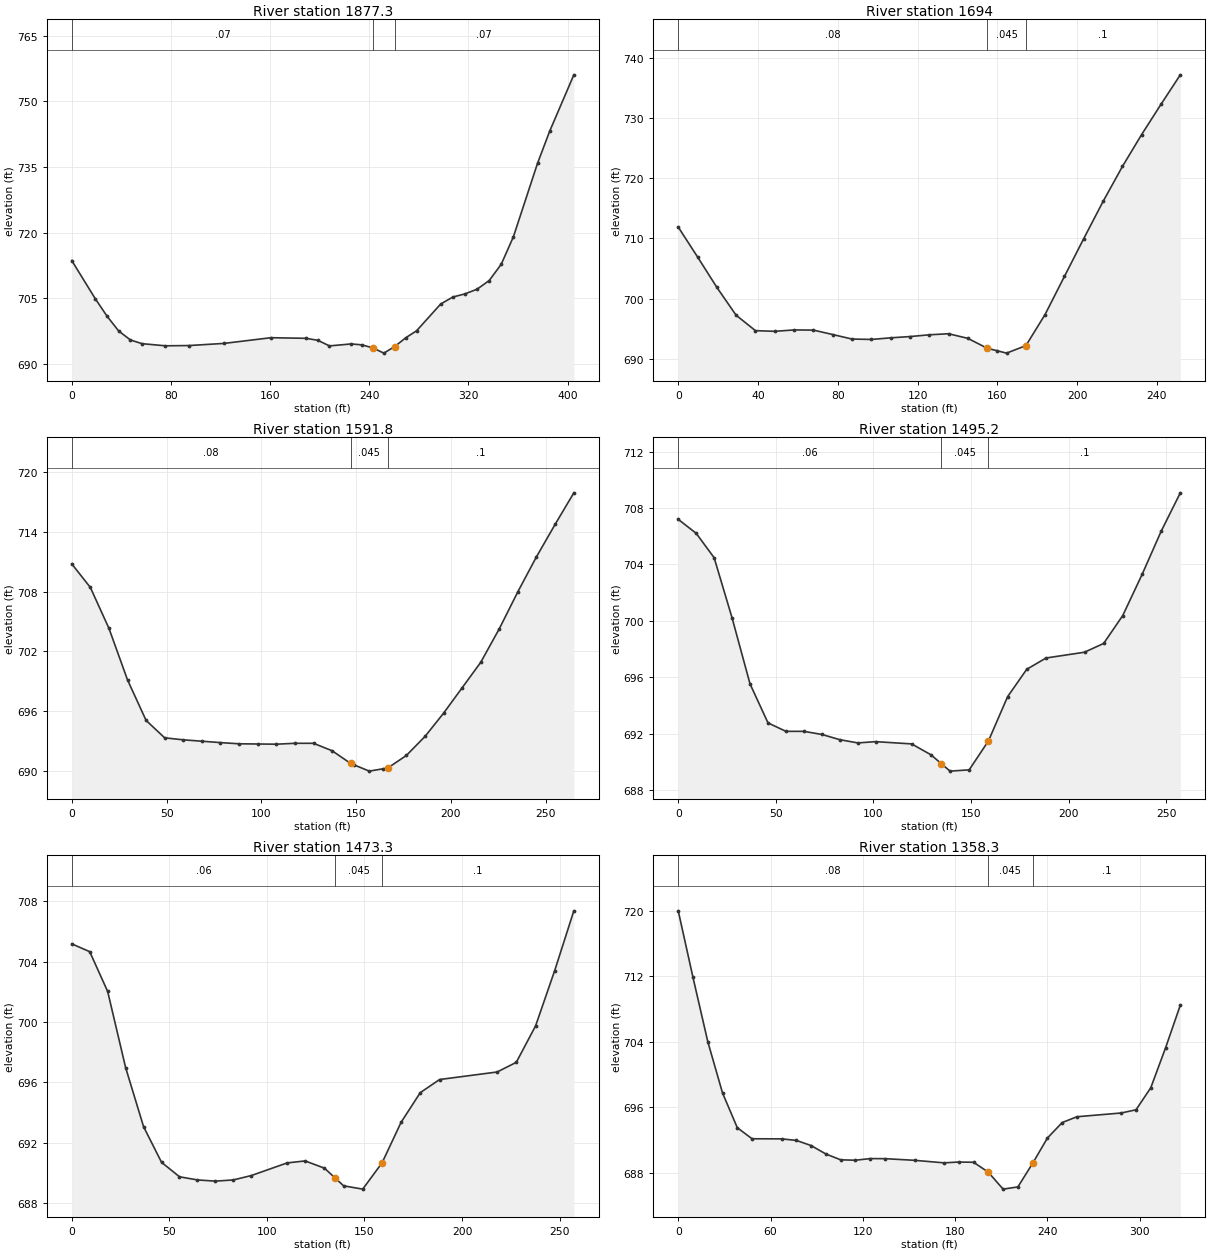
Type RM Length L Ch R = 1 ,1877.3  ,125.5,183.3,219.3
XS GIS Cut Line= 4
     1785069.406      472510.738     1785277.335      472512.046
     1785320.987      472457.013     1785447.323      472469.022
#Sta/Elev= 30
       0  713.63    18.9  704.95    28.4  700.96    37.8  697.57    47.3  695.51
    56.7  694.66    75.6  694.17    94.5  694.23   122.9  694.72   160.7  696.02
     189  695.88   198.5  695.43   207.9  694.15   225.5   694.6   234.3  694.38
     243  693.68   251.8   692.5   260.6  694.01   269.4  695.99   278.2   697.6
   297.7  703.72   307.5  705.31   317.2  706.02     327  707.09   336.8  709.07
   346.5  712.78   356.3  719.04   375.8  735.83   385.6  743.16   405.1  756.03
#Mann= 3 , 0 , 0
       0     .07       0     243    .045       0   260.6     .07       0
Bank Sta=243,260.6
XS Rating Curve= 0 ,0
Exp/Cntr=0.3,0.1

Type RM Length L Ch R = 1 ,1694    ,98.8,102.2,105.4
XS GIS Cut Line= 2
     1785067.934      472521.597     1785266.307      472676.528
#Sta/Elev= 29
       0  711.89     9.7  706.92    19.4  701.86      29  697.26    38.7  694.69
    48.4  694.58    58.1  694.81    67.8  694.78    77.4  694.05    87.1   693.3
    96.8  693.23   106.5   693.5   116.2  693.71   125.8     694   135.5  694.18
   145.2  693.41   154.9  691.77   159.6  691.38   164.6  690.96   174.3  692.21
   174.6  692.37   183.9  697.37   193.6  703.69   203.3  709.98     213  716.15
   222.7  721.96   232.3  727.24     242  732.26   251.7  737.16
#Mann= 3 , 0 , 0
       0     .08       0   154.9    .045       0   174.3      .1       0
Bank Sta=154.9,174.3
XS Rating Curve= 0 ,0
Exp/Cntr=0.3,0.1

Type RM Length L Ch R = 1 ,1591.8  ,94.9,96.6,98.6
XS GIS Cut Line= 2
     1785018.765       472582.44     1785201.404      472774.106
#Sta/Elev= 30
       0  710.79     9.8  708.42    19.6  704.31    29.4  699.12    39.2  695.04
      49  693.29    58.8  693.09    68.6  692.95    78.4  692.81    88.2  692.69
    98.1  692.67   107.9  692.65   117.7  692.74   127.5  692.74   137.3  691.99
   147.1  690.71     149  690.56   156.9  689.94     164  690.17   166.7  690.26
   176.5  691.52   186.3  693.43   196.1  695.77   205.9  698.33   215.7  700.89
   225.5  704.27   235.3     708   245.1  711.51     255  714.79   264.8  717.94
#Mann= 3 , 0 , 0
       0     .08       0   147.1    .045       0   166.7      .1       0
Bank Sta=147.1,166.7
XS Rating Curve= 0 ,0
Exp/Cntr=0.3,0.1

Type RM Length L Ch R = 1 ,1495.2  ,21.8,21.9,21.8
XS GIS Cut Line= 3
     1784971.564       472620.73     1785028.309      472726.048
     1785114.755      472833.227
#Sta/Elev= 27
       0   707.2     9.2  706.21    18.4  704.48    27.6  700.21    36.8  695.53
      46  692.77    55.2  692.17    64.4  692.17    73.6  691.95    82.8  691.58
      92  691.35   101.2  691.44   119.6  691.28   129.5  690.51   134.9689.8708
   139.3  689.35   149.1  689.44     159   691.5   168.8  694.63   178.6  696.57
   188.5  697.37   208.2  697.78     218   698.4   227.8  700.38   237.7  703.29
   247.5  706.36   257.3  709.08
#Mann= 3 , 0 , 0
       0     .06       0   134.9    .045       0     159      .1       0
Bank Sta=134.9,159
XS Rating Curve= 0 ,0
Exp/Cntr=0.3,0.1

Type RM Length L Ch R = 1 ,1473.3  ,109.6,115,119.8
XS GIS Cut Line= 3
     1784952.043      472630.717     1785008.788      472736.035
     1785095.234      472843.214
#Sta/Elev= 26
       0  705.18     9.2  704.66    18.4  702.02    27.6  696.97    36.8  693.05
      46  690.69    55.2  689.73    64.4  689.52    73.6  689.44    82.8  689.52
      92  689.81   110.4  690.65   119.6  690.78   129.5   690.3   135.1689.6314
   139.3  689.13   149.1  688.91     159  690.65   168.8  693.35   178.6  695.31
   188.5  696.18     218  696.68   227.8  697.32   237.7  699.74   247.5  703.41
   257.3  707.37
#Mann= 3 , 0 , 0
       0     .06       0   135.1    .045       0     159      .1       0
Bank Sta=135.1,159
XS Rating Curve= 0 ,0
Exp/Cntr=0.3,0.1

Type RM Length L Ch R = 1 ,1358.3  ,79.4,80,80.8
XS GIS Cut Line= 2
     1784835.606      472625.683     1784978.403      472919.243
#Sta/Elev= 30
       0  720.02     9.6  711.88    19.2  704.05    28.8  697.77    38.4  693.53
      48  692.18    67.2  692.17    76.8  691.98    86.4  691.35      96  690.32
   105.6  689.61   115.2  689.56   124.8  689.76   134.4  689.75   153.6  689.55
   172.8  689.24   182.4  689.34     192  689.31   201.5688.1126   211.2  686.03
   220.8   686.3   230.4  689.18     240  692.27   249.6  694.16   259.2  694.87
     288  695.33   297.6  695.72   307.2  698.41   316.8  703.28   326.4   708.5
#Mann= 3 , 0 , 0
       0     .08       0   201.5    .045       0   230.4      .1       0
Bank Sta=201.5,230.4
XS Rating Curve= 0 ,0
Exp/Cntr=0.3,0.1

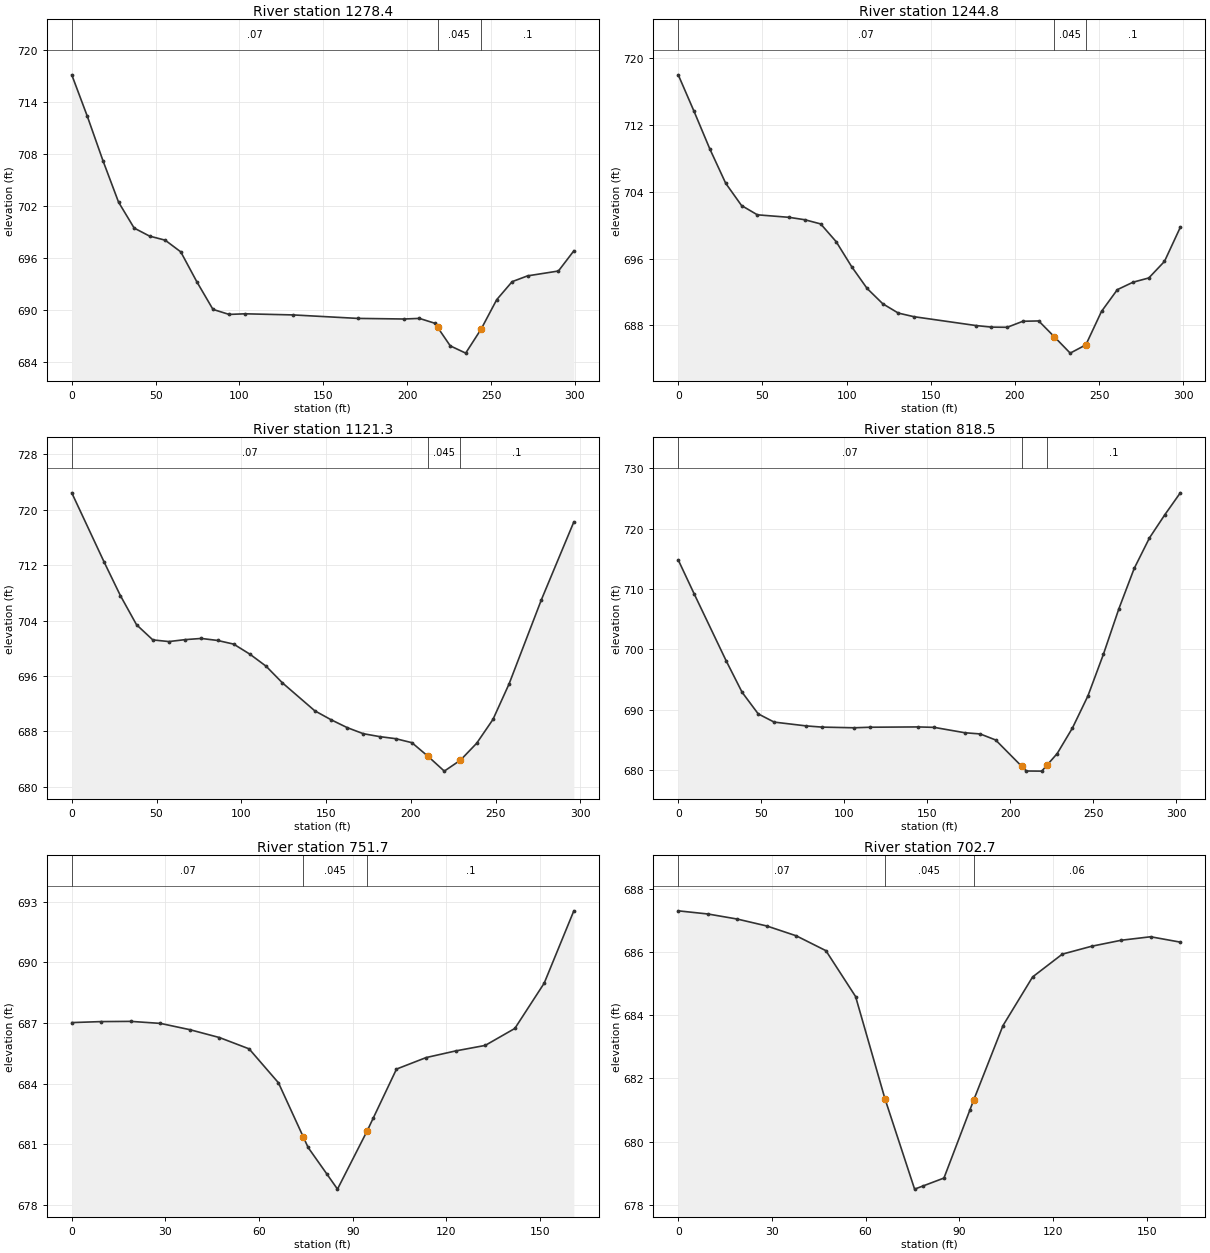
Type RM Length L Ch R = 1 ,1278.4  ,33.7,33.5,33.4
XS GIS Cut Line= 4
      1784717.06      472687.102     1784745.954      472745.359
     1784834.922      472801.859     1784887.512      472919.668
#Sta/Elev= 26
       0  717.14     9.3  712.34    18.6  707.23    27.9  702.44    37.2  699.45
    46.4  698.52    55.7  698.05      65   696.7    74.6  693.24    84.2  690.06
    93.8  689.48   103.4  689.55   132.1  689.42   170.4  689.02   198.1  688.95
   207.3  689.02   216.5  688.46   218.2687.9777   225.7  685.85   234.9  685.01
   244.1  687.78   253.4  691.18   262.6  693.26   271.8  693.93   290.2  694.49
   299.4  696.82
#Mann= 3 , 0 , 0
       0     .07       0   218.2    .045       0   244.1      .1       0
Bank Sta=218.2,244.1
XS Rating Curve= 0 ,0
Exp/Cntr=0.3,0.1

Type RM Length L Ch R = 1 ,1244.8  ,124.8,123.6,122.4
XS GIS Cut Line= 4
     1784685.763      472696.732     1784723.396      472772.486
     1784809.046      472826.827      1784855.35      472928.968
#Sta/Elev= 29
       0  717.97     9.4   713.6    18.8  709.09    28.2     705    37.6  702.34
      47  701.23    65.8  700.93    75.2  700.64    84.6  700.14    93.8  698.02
     103  695.03   112.2  692.42   121.5  690.59   130.7  689.48   139.9  689.05
   176.8  687.99     186   687.8   195.4  687.78   204.7   688.5   214.1  688.54
   223.4  686.64   232.8  684.69   242.1  685.68   251.4  689.68   260.8  692.28
   270.1  693.17   279.5  693.68   288.8  695.66   298.2  699.74
#Mann= 3 , 0 , 0
       0     .07       0   223.4    .045       0   242.1      .1       0
Bank Sta=223.4,242.1
XS Rating Curve= 0 ,0
Exp/Cntr=0.3,0.1

Type RM Length L Ch R = 1 ,1121.3  ,292.5,302.8,313
XS GIS Cut Line= 2
     1784612.574      472717.918      1784748.84      472980.819
#Sta/Elev= 28
       0  722.46    19.1  712.45    28.7   707.6    38.2   703.4    47.8  701.21
    57.3  700.97    66.9  701.25    76.4  701.42      86  701.13    95.5   700.6
   105.1  699.14   114.6  697.41   124.2  695.01   143.3  690.97   152.8  689.69
   162.4  688.54   171.9  687.66   181.5  687.24     191  686.94   200.6  686.36
   210.2  684.37   219.7  682.25   229.2  683.83   238.8  686.28   248.4  689.72
   257.9  694.85     277  707.04   296.1  718.26
#Mann= 3 , 0 , 0
       0     .07       0   210.2    .045       0   229.2      .1       0
Bank Sta=210.2,229.2
XS Rating Curve= 0 ,0
Exp/Cntr=0.3,0.1

Type RM Length L Ch R = 1 ,818.5   ,65.5,66.8,67.9
XS GIS Cut Line= 3
      1784387.51      472814.486      1784437.51       472960.32
     1784440.982      473108.693
#Sta/Elev= 28
       0  714.81     9.6   709.2    28.9  698.12    38.5  692.92    48.2  689.35
    57.8  687.99    77.1  687.36    86.7  687.16     106  687.05   115.6  687.14
   144.5  687.19   154.2  687.12   172.7  686.23     182  686.03   191.3  685.03
   207.1  680.65   209.8   679.9   219.1  679.88   222.1  680.82   228.4  682.79
   237.6  687.02   246.9  692.31   256.2  699.17   265.5  706.68   274.8   713.4
     284  718.45   293.3   722.3   302.6  725.91
#Mann= 3 , 0 , 0
       0     .07       0   207.1    .045       0   222.1      .1       0
Bank Sta=207.1,222.1
XS Rating Curve= 0 ,0
Exp/Cntr=0.3,0.1

Type RM Length L Ch R = 1 ,751.7   ,48.9,48.9,48.9
XS GIS Cut Line= 2
     1784375.061      472926.698     1784370.068        473087.4
#Sta/Elev= 21
       0  687.02     9.5  687.07    18.9  687.08    28.4  686.98    37.8  686.67
    47.3  686.28    56.8  685.72    66.2  684.04    74.1 681.379    75.7  680.84
    81.6  679.55    85.1  678.78    94.6  681.66    96.6  682.31     104  684.72
   113.5  685.29     123  685.62   132.4  685.89   141.9  686.73   151.3  688.97
   160.8  692.55
#Mann= 3 , 0 , 0
       0     .07       0    74.1    .045       0    94.6      .1       0
Bank Sta=74.1,94.6
XS Rating Curve= 0 ,0
Exp/Cntr=0.3,0.1

Type RM Length L Ch R = 1 ,702.7   ,191.5,180.6,169.6
XS GIS Cut Line= 2
     1784326.034      472928.968      1784321.04      473089.669
#Sta/Elev= 20
       0   687.3     9.5   687.2    18.9  687.04    28.4  686.82    37.8  686.51
    47.3  686.04    56.8  684.59    66.2  681.36    75.7   678.5    78.4   678.6
    85.1  678.85    93.4     681    94.6  681.31     104  683.67   113.5  685.21
     123  685.93   132.4  686.18   141.9  686.37   151.3  686.48   160.8  686.31
#Mann= 3 , 0 , 0
       0     .07       0    66.2    .045       0    94.6     .06       0
Bank Sta=66.2,94.6
XS Rating Curve= 0 ,0
Exp/Cntr=0.3,0.1

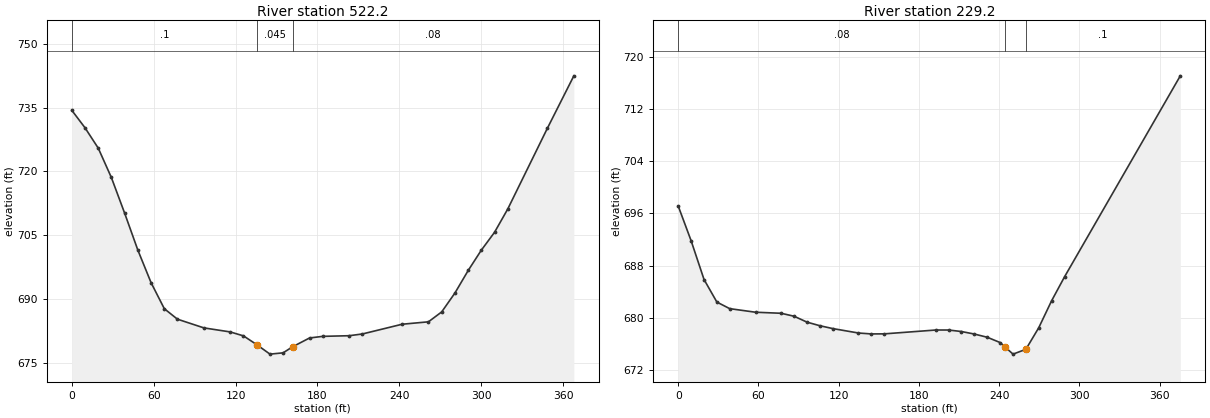
Type RM Length L Ch R = 1 ,522.2   ,296.5,293,289.4
XS GIS Cut Line= 2
     1784085.369      472921.396     1784247.305      473251.598
#Sta/Elev= 30
       0  734.35     9.7  730.23    19.4  725.44      29  718.54    38.7  710.18
    48.4  701.47    58.1   693.8    67.8  687.68    77.4  685.22    96.8  683.17
   116.1  682.22   125.8  681.29   135.5  679.23   145.2     677   154.8   677.3
   161.7678.7156   174.2   680.8   183.9  681.18   203.2  681.33   212.9  681.74
     242  684.03   261.3   684.6     271  686.93   280.7  691.38   290.4  696.67
     300  701.44   309.7  705.65   319.4  711.14   348.4  730.11   367.8  742.45
#Mann= 3 , 0 , 0
       0      .1       0   135.5    .045       0   161.7     .08       0
Bank Sta=135.5,161.7
XS Rating Curve= 0 ,0
Exp/Cntr=0.3,0.1

Type RM Length L Ch R = 1 ,229.2   ,235.9,229.2,222.4
XS GIS Cut Line= 2
     1783780.647      473032.141     1783996.525       473339.42
#Sta/Elev= 27
       0  697.12     9.6  691.82    19.3  685.85    28.9  682.39    38.5  681.38
    57.8  680.83      77  680.67    86.7  680.21    96.3  679.31   105.9  678.76
   115.6  678.32   134.8  677.64   144.4   677.5   154.1  677.51   192.6   678.1
   202.2   678.1   211.8  677.87   221.5  677.48   231.1  676.99   240.7  676.18
   244.6675.4644   250.4   674.4     260  675.14   269.6  678.44   279.2  682.57
   288.9  686.26   375.5  717.11
#Mann= 3 , 0 , 0
       0     .08       0   244.6    .045       0     260      .1       0
Bank Sta=244.6,260
XS Rating Curve= 0 ,0
Exp/Cntr=0.3,0.1

Chan Stop Cuts=-1
Use User Specified Reach Order=0
Composite Channel Slope=5

--- CANEFORK1.g02 (geometry) ---

Geom Title=USGS 10m DEM_copy
Program Version=4.10

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
River Reach=CANEFORK1       ,Main