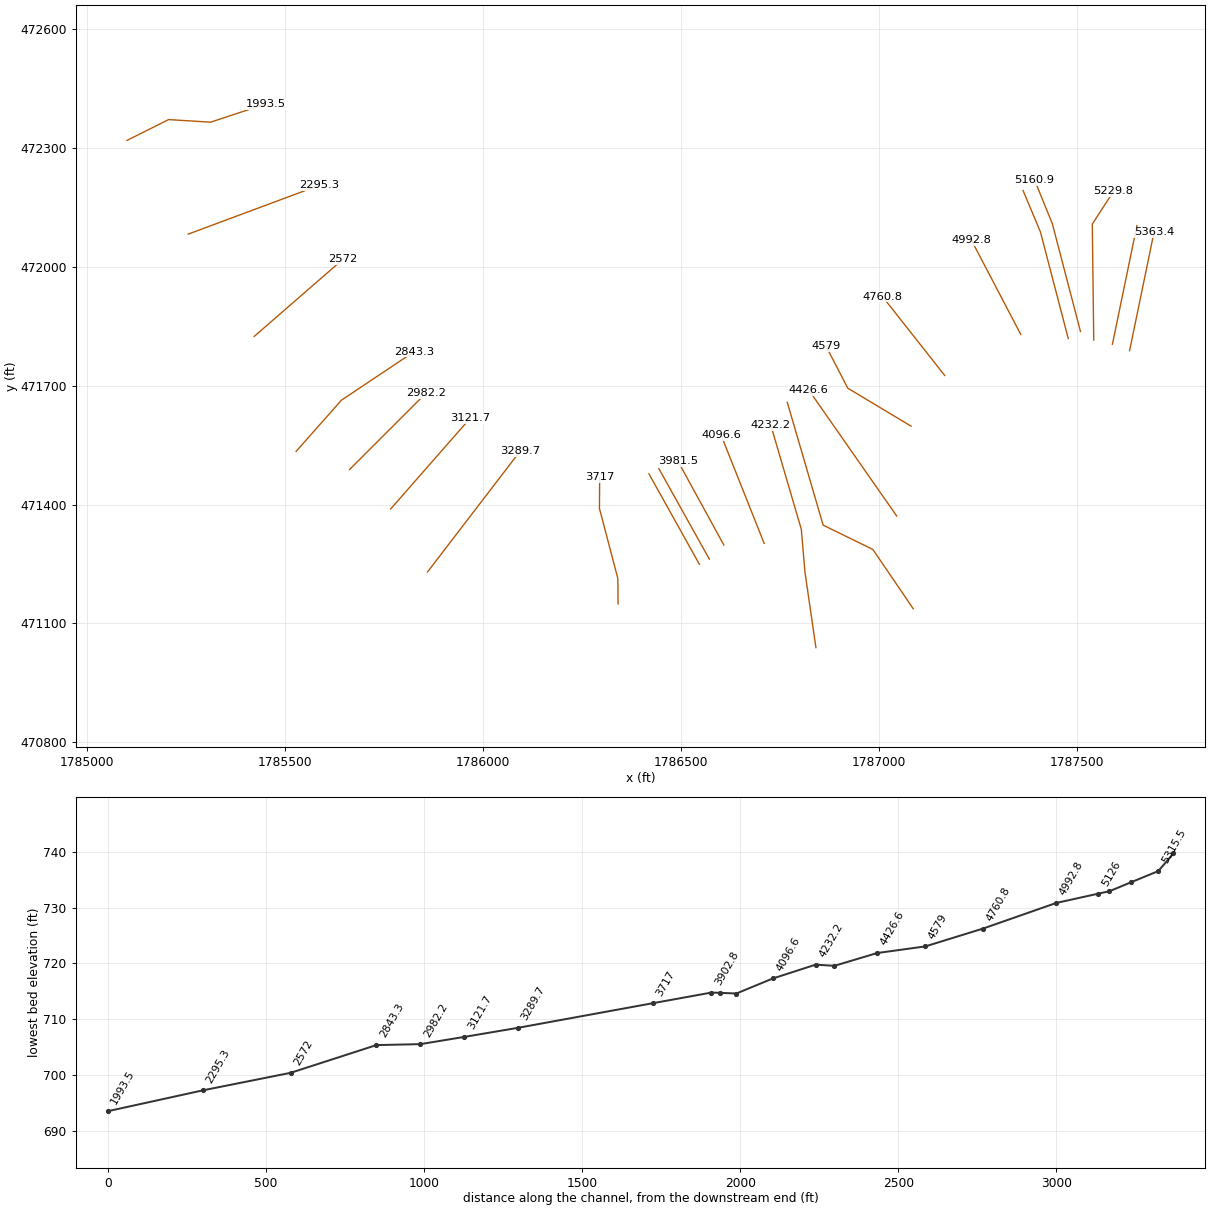
HEC-RAS study CANEFORK1.prj: CANEFORK1

--- CANEFORK1.g02 (geometry) --- (continued)

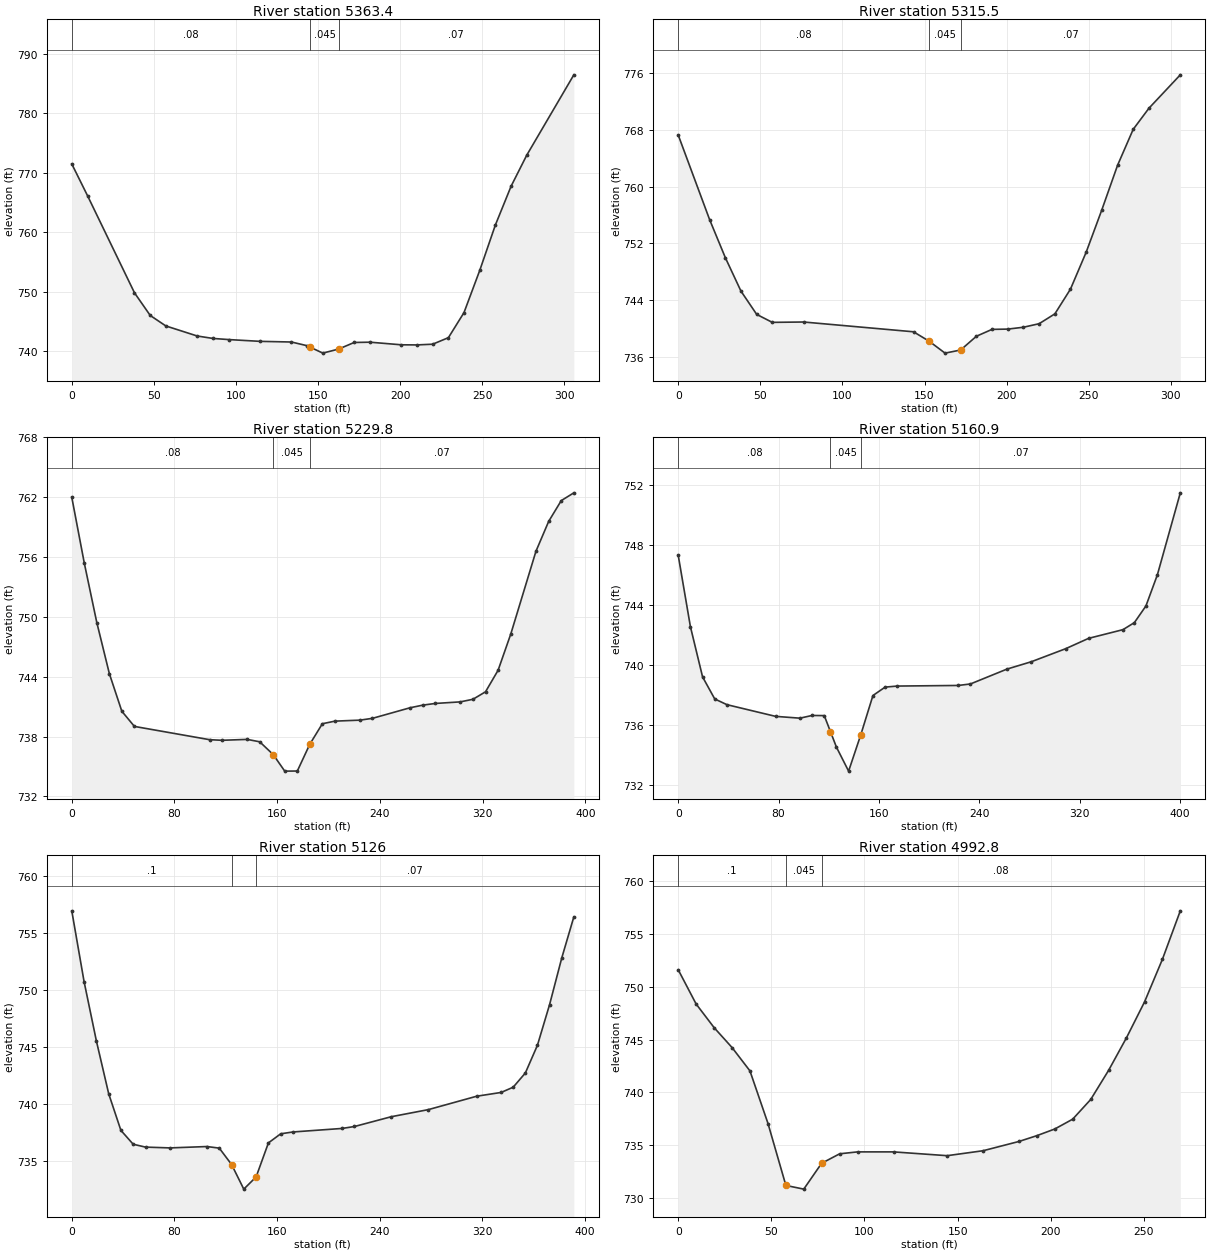
Type RM Length L Ch R = 1 ,5363.4  ,48,48,47.8
XS GIS Cut Line= 2
     1787633.658      471788.735     1787695.507      472088.214
#Sta/Elev= 26
       0  771.52     9.6  766.17    38.2  749.84    47.8  746.03    57.3  744.27
    76.4  742.58      86  742.17    95.6  741.98   114.7  741.68   133.8  741.57
   143.3  740.95   145.3  740.69   152.9   739.7   162.5  740.38     172  741.49
   181.6  741.54   200.7   741.1   210.2  741.08   219.8   741.2   229.4   742.3
   238.9  746.52   248.5  753.62     258  761.24   267.6  767.78   277.1  772.98
   305.8   786.5
#Mann= 3 , 0 , 0
       0     .08       0   145.3    .045       0   162.5     .07       0
Bank Sta=145.3,162.5
XS Rating Curve= 0 ,0
Exp/Cntr=0.3,0.1

Type RM Length L Ch R = 1 ,5315.5  ,79.3,85.7,92
XS GIS Cut Line= 2
     1787590.312      471805.154     1787652.161      472104.633
#Sta/Elev= 24
       0  767.29    19.1  755.37    28.7  749.99    38.2  745.28    47.8  741.99
    57.3  740.87    76.4  740.92   143.3  739.54   152.9   738.2   162.5  736.53
     172  736.97   181.6  738.91   191.1  739.88   200.7  739.92   210.2  740.18
   219.8  740.68   229.4  742.07   238.9  745.56   248.5  750.79     258  756.74
   267.6  763.04   277.1   768.1   286.7  771.08   305.8  775.79
#Mann= 3 , 0 , 0
       0     .08       0   152.9    .045       0     172     .07       0
Bank Sta=152.9,172
XS Rating Curve= 0 ,0
Exp/Cntr=0.3,0.1

Type RM Length L Ch R = 1 ,5229.8  ,61.6,68.9,76.2
XS GIS Cut Line= 3
     1787543.161      471815.647     1787539.517      472108.411
     1787592.834      472191.055
#Sta/Elev= 30
       0  761.99     9.8  755.36    19.5  749.43    29.3   744.3      39  740.54
    48.8  739.02   107.4  737.69   117.1  737.63   136.6  737.72   146.4  737.48
   156.9   736.2   165.9  734.54   175.7  734.55   185.4  737.23   195.2  739.29
     205  739.55   224.5  739.65   234.2  739.83   263.5  740.89   273.3  741.15
     283  741.32   302.6  741.48   312.5  741.74   322.3  742.49   332.1  744.65
     342  748.29   361.6  756.58   371.5  759.57   381.3  761.65   391.1  762.43
#Mann= 3 , 0 , 0
       0     .08       0   156.9    .045       0   185.4     .07       0
Bank Sta=156.9,185.4
XS Rating Curve= 0 ,0
Exp/Cntr=0.3,0.1

Type RM Length L Ch R = 1 ,5160.9  ,35,35,35
XS GIS Cut Line= 3
     1787509.603      471837.363     1787438.526      472109.614
     1787393.701      472219.629
#Sta/Elev= 27
       0   747.3     9.7  742.55    19.4   739.2    29.1  737.73    38.8  737.35
    77.6  736.57      97  736.45   106.7  736.63   116.4  736.62   121.3  735.56
   126.1  734.52   135.8  732.92   145.5  735.34   155.2  737.96   164.9  738.52
   174.6  738.59   223.2  738.63   232.9  738.73     262  739.72   281.4  740.21
   308.8  741.08   327.1  741.77   354.5  742.35   363.6  742.82   372.8  743.93
   381.9     746   400.2  751.47
#Mann= 3 , 0 , 0
       0     .08       0   121.3    .045       0   145.5     .07       0
Bank Sta=121.3,145.5
XS Rating Curve= 0 ,0
Exp/Cntr=0.3,0.1

Type RM Length L Ch R = 1 ,5126    ,126.2,133.2,139.9
XS GIS Cut Line= 3
     1787478.736      471819.631     1787408.544       472088.49
     1787364.688      472193.253
#Sta/Elev= 28
       0  756.93     9.6  750.71    19.2   745.5    28.8  740.86    38.3  737.65
    47.9  736.43    57.5  736.18    76.6  736.11   105.4  736.23     115  736.09
   124.6  734.65   134.1  732.49   143.7  733.56   153.3  736.55   162.9  737.35
   172.5  737.51   210.8  737.82   220.4  737.99   249.1  738.85   277.9  739.47
   315.7  740.65   334.7  740.98   344.1  741.44   353.6  742.69     363  745.12
   372.5   748.7     382   752.8   391.4   756.4
#Mann= 3 , 0 , 0
       0      .1       0   124.6    .045       0   143.7     .07       0
Bank Sta=124.6,143.7
XS Rating Curve= 0 ,0
Exp/Cntr=0.3,0.1

Type RM Length L Ch R = 1 ,4992.8  ,226.3,232,237.5
XS GIS Cut Line= 2
     1787358.925      471829.612     1787233.925      472068.501
#Sta/Elev= 24
       0  751.61     9.6  748.37    19.3  746.12    28.9  744.24    38.5  742.03
    48.2  737.04    57.8  731.17    67.4  730.82      77  733.27    86.7  734.17
    96.3  734.35   115.6  734.35   144.4  733.99   163.7  734.46     183  735.34
   192.6  735.89   202.2  736.52   211.8  737.45   221.5  739.32   231.1  742.08
   240.7  745.17   250.4  748.57     260  752.61   269.6   757.2
#Mann= 3 , 0 , 0
       0      .1       0    57.8    .045       0      77     .08       0
Bank Sta=57.8,77
XS Rating Curve= 0 ,0
Exp/Cntr=0.3,0.1

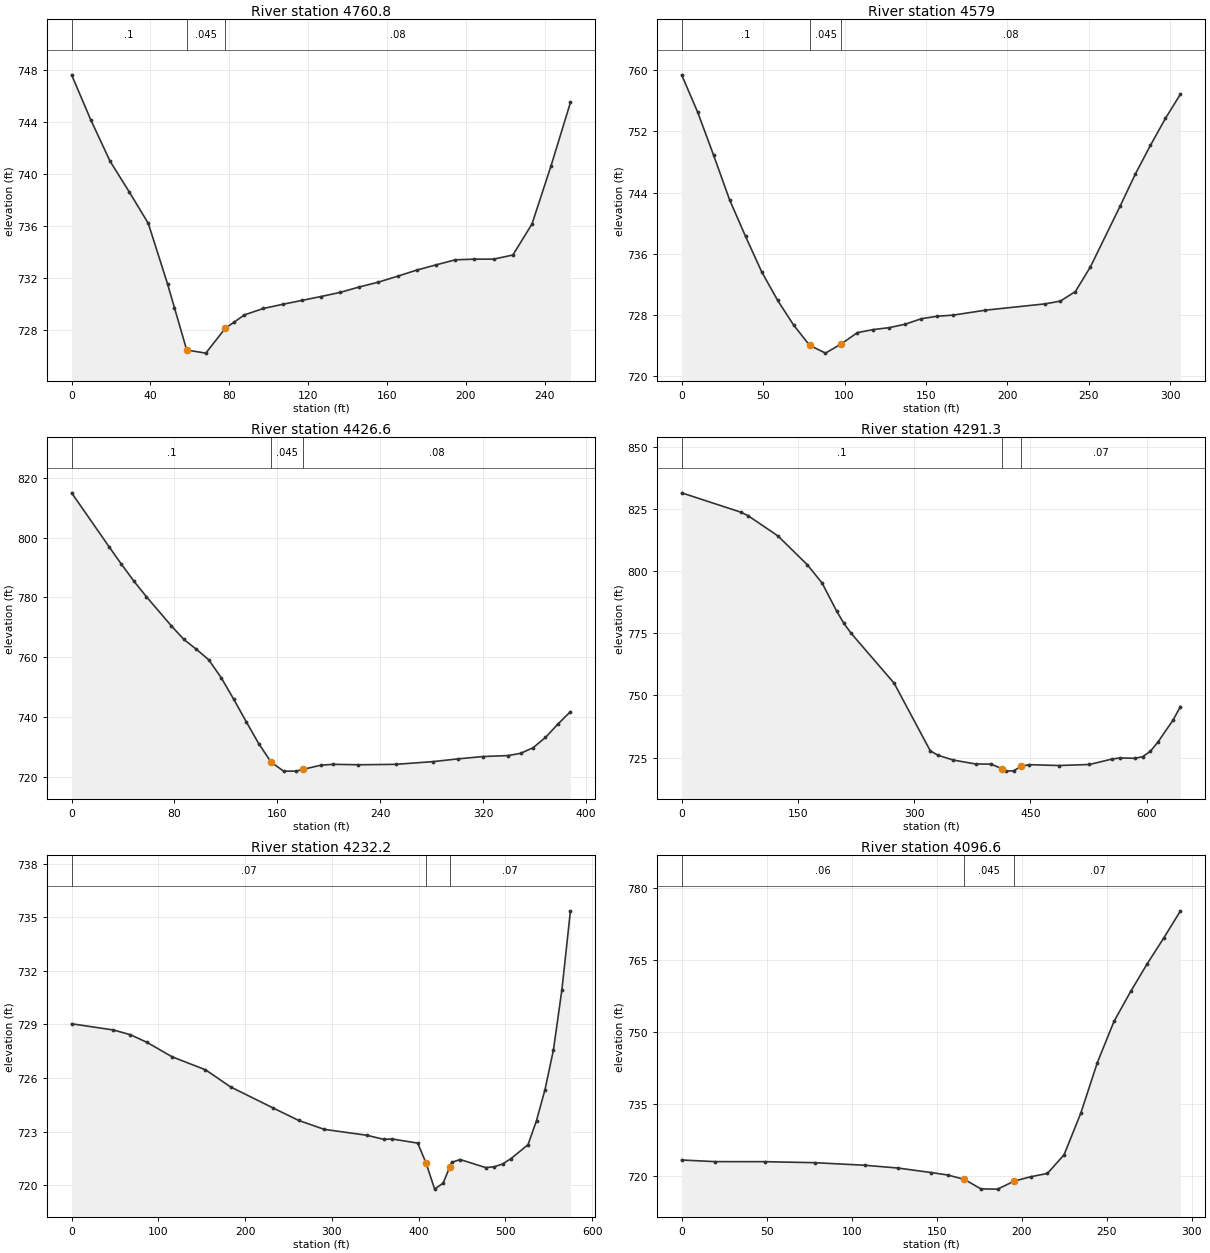
Type RM Length L Ch R = 1 ,4760.8  ,170.6,181.7,192.3
XS GIS Cut Line= 2
     1787166.737      471726.159      1787010.02      471924.848
#Sta/Elev= 29
       0  747.66     9.7   744.2    19.5  741.01    29.2  738.65    38.9  736.22
    48.7  731.54    52.2  729.71    58.4  726.46    68.1  726.22    77.9  728.12
    82.2  728.58    87.6  729.16    97.3  729.66   107.1  729.98   116.8  730.28
   126.5  730.58   136.3   730.9     146  731.32   155.7  731.69   165.5  732.15
   175.2  732.62   184.9  733.02   194.7  733.41   204.4  733.46   214.1  733.46
   223.9  733.78   233.6  736.17   243.3  740.67   253.1  745.53
#Mann= 3 , 0 , 0
       0      .1       0    58.4    .045       0    77.9     .08       0
Bank Sta=58.4,77.9
XS Rating Curve= 0 ,0
Exp/Cntr=0.3,0.1

Type RM Length L Ch R = 1 ,4579    ,165,152.4,139.6
XS GIS Cut Line= 3
     1787081.807      471598.087      1786921.96      471693.995
     1786866.833      471800.322
#Sta/Elev= 28
       0   759.4     9.8  754.54    19.6  748.91    29.4  743.09    39.2   738.3
    49.1  733.68    58.9  729.94    68.7  726.72    78.5  724.07    88.3  723.04
    98.1  724.26   107.9  725.72   117.7  726.12   127.5  726.37   137.4  726.83
   147.2  727.54     157  727.86   166.8  728.01   186.4  728.65   223.3  729.48
   232.5  729.84   241.7  731.09   250.9   734.3   269.3  742.31   278.5  746.44
   287.8   750.2     297  753.72   306.2  756.88
#Mann= 3 , 0 , 0
       0      .1       0    78.5    .045       0    98.1     .08       0
Bank Sta=78.5,98.1
XS Rating Curve= 0 ,0
Exp/Cntr=0.3,0.1

Type RM Length L Ch R = 1 ,4426.6  ,145.1,135.3,125.5
XS GIS Cut Line= 2
     1787045.399      471371.293      1786823.32      471689.435
#Sta/Elev= 30
       0  814.95    29.1  796.94    38.8  791.03    48.5  785.38    58.2   780.2
    77.6  770.44    87.3  765.91      97  762.63   106.7  759.08   116.4  753.08
   126.1   745.9   135.8  738.41   145.5  731.09   155.2  724.84   164.9  721.85
   174.6  721.85   180.3  722.48     194  723.84   203.7  724.13   223.1  723.98
   252.2  724.12   281.3  725.04   300.7  725.96   320.1  726.73   339.5  727.06
   349.2   727.8   358.9  729.67   368.6  733.12   378.3  737.61     388  741.74
#Mann= 3 , 0 , 0
       0      .1       0   155.2    .045       0   180.3     .08       0
Bank Sta=155.2,180.3
XS Rating Curve= 0 ,0
Exp/Cntr=0.3,0.1

Type RM Length L Ch R = 1 ,4291.3  ,58.9,59.2,60.1
XS GIS Cut Line= 4
     1787087.126      471137.078     1786985.171       471286.82
       1786859.7      471348.083     1786769.175      471657.981
#Sta/Elev= 30
       0  831.54    76.3  823.76    85.8  822.32     124  814.26   162.1  802.61
   181.2  795.26   199.8  784.06   209.1  779.12   218.4  775.13   274.2  754.92
   320.8  727.72   330.6  725.97   350.1  724.04   379.5  722.43     399  722.39
   412.8  720.61   418.6  719.56   428.4  719.71   438.2  721.49     448  722.16
   487.1  721.82   526.2  722.24   555.6  724.44   565.4  724.85   584.9  724.73
   594.7  725.34   604.5  727.46   614.3  731.17   633.8     740   643.6  745.54
#Mann= 3 , 0 , 0
       0      .1       0   412.8    .045       0   438.2     .07       0
Bank Sta=412.8,438.2
XS Rating Curve= 0 ,0
Exp/Cntr=0.3,0.1

Type RM Length L Ch R = 1 ,4232.2  ,132.5,135.5,137.6
XS GIS Cut Line= 4
     1786841.467      471038.814     1786813.747      471229.702
     1786804.549      471337.487     1786727.575      471600.276
#Sta/Elev= 30
       0  729.04    48.2  728.69    67.5  728.43    86.8     728   115.7  727.19
   154.3  726.46   183.2   725.5   232.2  724.32   261.7  723.62   291.2  723.12
   340.2  722.79   359.7  722.56   369.5  722.58   398.9  722.35   408.6  721.22
   418.4  719.77   428.2  720.11     436  721.03     438  721.27   447.8  721.43
   477.1  720.98   486.9  721.02   496.7  721.18   506.4  721.48     526  722.26
   535.8  723.61   545.6  725.35   555.3  727.57   565.1  730.96   574.9  735.37
#Mann= 3 , 0 , 0
       0     .07       0   408.6    .045       0     436     .07       0
Bank Sta=408.6,436
XS Rating Curve= 0 ,0
Exp/Cntr=0.3,0.1

Type RM Length L Ch R = 1 ,4096.6  ,111.3,115.2,118.7
XS GIS Cut Line= 2
       1786710.7       471302.12     1786602.184      471574.821
#Sta/Elev= 22
       0  723.35    19.6  723.01    48.9     723    78.3  722.79   107.6  722.26
   127.2  721.68   146.8  720.74   156.5  720.23   166.3  719.33   176.1  717.34
   185.9  717.29   195.7  718.96   205.4  719.87   215.2  720.55     225  724.43
   234.8  733.04   244.6  743.62   254.4  752.19   264.2  758.41   273.9  764.15
   283.7  769.55   293.5  775.18
#Mann= 3 , 0 , 0
       0     .06       0   166.3    .045       0   195.7     .07       0
Bank Sta=166.3,195.7
XS Rating Curve= 0 ,0
Exp/Cntr=0.3,0.1

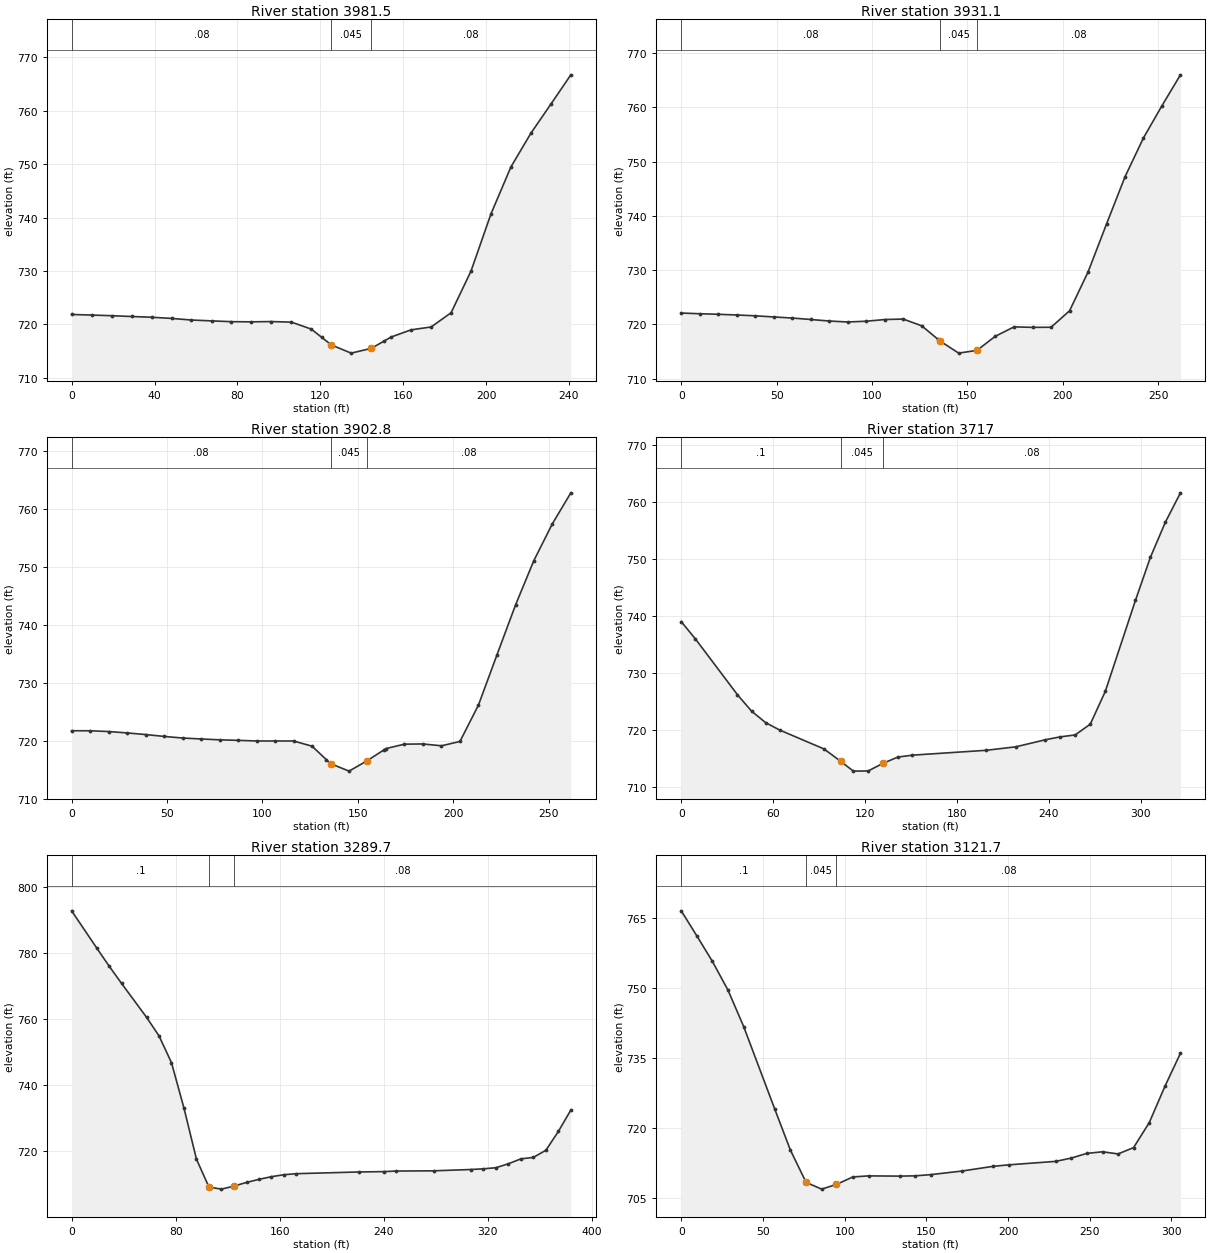
Type RM Length L Ch R = 1 ,3981.5  ,50.2,50.4,50.6
XS GIS Cut Line= 2
     1786608.928      471297.774     1786493.222      471509.084
#Sta/Elev= 28
       0  721.84     9.6  721.73    19.3  721.61    28.9  721.46    38.6  721.32
    48.2   721.1    57.8   720.8    67.5  720.64    77.1  720.49    86.7  720.46
    96.4  720.51     106  720.41   115.6  719.11   120.7  717.55   125.3  716.14
   134.9   714.6   144.6  715.49   150.7  716.84   154.2  717.62   163.8  718.96
   173.5   719.5   183.1  722.16   192.7  729.94   202.4  740.72     212  749.48
   221.6  755.77   231.3  761.25   240.9  766.72
#Mann= 3 , 0 , 0
       0     .08       0   125.3    .045       0   144.6     .08       0
Bank Sta=125.3,144.6
XS Rating Curve= 0 ,0
Exp/Cntr=0.3,0.1

Type RM Length L Ch R = 1 ,3931.1  ,28.3,28.3,28.3
XS GIS Cut Line= 2
     1786572.157      471262.474     1786444.685      471490.944
#Sta/Elev= 29
       0  722.11     9.7  721.98    19.4  721.88    29.1  721.75    38.8   721.6
    48.4  721.39    58.1  721.19    67.8  720.92    77.5  720.64    87.2  720.46
    96.9   720.6   106.6  720.91   116.3     721     126  719.76   134.5  717.28
   135.7  716.93   145.4  714.72     155  715.23   164.5  717.81   174.4  719.56
   184.1  719.47   193.8  719.49   203.5  722.53   213.2  729.69   222.9  738.56
   232.6  747.27   242.2  754.38   251.9  760.32   261.6  766.02
#Mann= 3 , 0 , 0
       0     .08       0   135.7    .045       0     155     .08       0
Bank Sta=135.7,155
XS Rating Curve= 0 ,0
Exp/Cntr=0.3,0.1

Type RM Length L Ch R = 1 ,3902.8  ,193.1,185.8,177.4
XS GIS Cut Line= 2
     1786547.153      471249.237     1786419.681      471477.706
#Sta/Elev= 30
       0  721.74     9.7  721.73    19.4   721.6    29.1  721.36    38.8  721.08
    48.4  720.76    58.1  720.48    67.8  720.32    77.5  720.17    87.2  720.08
    96.9  719.97   106.6  719.97   116.3  719.97     126  719.07   133.5  716.74
   135.7  716.06   145.4  714.77     155  716.59   163.5   718.4   164.7  718.66
   174.4  719.42   184.1  719.46   193.8  719.14   203.5  719.89   213.2  726.18
   222.9  734.84   232.6  743.42   242.2  751.08   251.9  757.43   261.6  762.78
#Mann= 3 , 0 , 0
       0     .08       0   135.7    .045       0     155     .08       0
Bank Sta=135.7,155
XS Rating Curve= 0 ,0
Exp/Cntr=0.3,0.1

Type RM Length L Ch R = 1 ,3717    ,454.8,427.3,400.2
XS GIS Cut Line= 4
     1786341.727      471149.045     1786341.173      471213.275
     1786294.661      471390.462     1786295.215      471469.088
#Sta/Elev= 24
       0  739.05     9.2  736.05    36.7  726.25    45.9  723.38    55.1  721.36
    64.2  720.07    93.2  716.75   104.2  714.57   112.4  712.86   122.1  712.89
   131.7  714.22   141.4  715.32     151  715.66   199.2  716.51   218.5  717.12
   237.8  718.36   247.4  718.86   257.2   719.2   267.1  721.08   276.9  726.82
   296.6  742.77   306.4  750.35   316.2  756.51     326  761.63
#Mann= 3 , 0 , 0
       0      .1       0   104.2    .045       0   131.7     .08       0
Bank Sta=104.2,131.7
XS Rating Curve= 0 ,0
Exp/Cntr=0.3,0.1

Type RM Length L Ch R = 1 ,3289.7  ,170.1,168.1,166.1
XS GIS Cut Line= 2
     1785860.414      471229.788     1786093.921      471534.475
#Sta/Elev= 30
       0  792.82    19.2   781.6    28.8  776.08    38.4  770.81    57.6  760.55
    67.2  754.91    76.8  746.77    86.4  732.99      96  717.53   105.6  709.07
   115.2  708.44   124.8  709.36   134.8   710.5     144   711.4   153.6  712.21
   163.2   712.8   172.7  713.12   220.7  713.64   239.9  713.75   249.5  713.92
   278.3  713.99   307.1  714.39   316.7   714.6   326.3  714.93   335.9  716.14
   345.5  717.62   355.1  718.06   364.7  720.22   374.3  725.93   383.9  732.42
#Mann= 3 , 0 , 0
       0      .1       0   105.6    .045       0   124.8     .08       0
Bank Sta=105.6,124.8
XS Rating Curve= 0 ,0
Exp/Cntr=0.3,0.1

Type RM Length L Ch R = 1 ,3121.7  ,141.4,139.4,137.5
XS GIS Cut Line= 2
      1785767.15      471388.719      1785968.47      471618.496
#Sta/Elev= 27
       0  766.51     9.6  761.11    19.1  755.65    28.6  749.51    38.2   741.7
    57.3  723.93    66.8   715.2    76.4  708.28    85.9  706.83    94.9  707.83
     105  709.44   114.6  709.67   133.6  709.62   143.2  709.68   152.8  709.94
   171.8  710.71   190.9  711.72   200.5  712.04   229.1  712.78   238.7  713.49
   248.2  714.49   257.8  714.84   267.3  714.38   276.8  715.73   286.4  721.08
     296  728.88   305.5  735.97
#Mann= 3 , 0 , 0
       0      .1       0    76.4    .045       0    94.9     .08       0
Bank Sta=76.4,94.9
XS Rating Curve= 0 ,0
Exp/Cntr=0.3,0.1

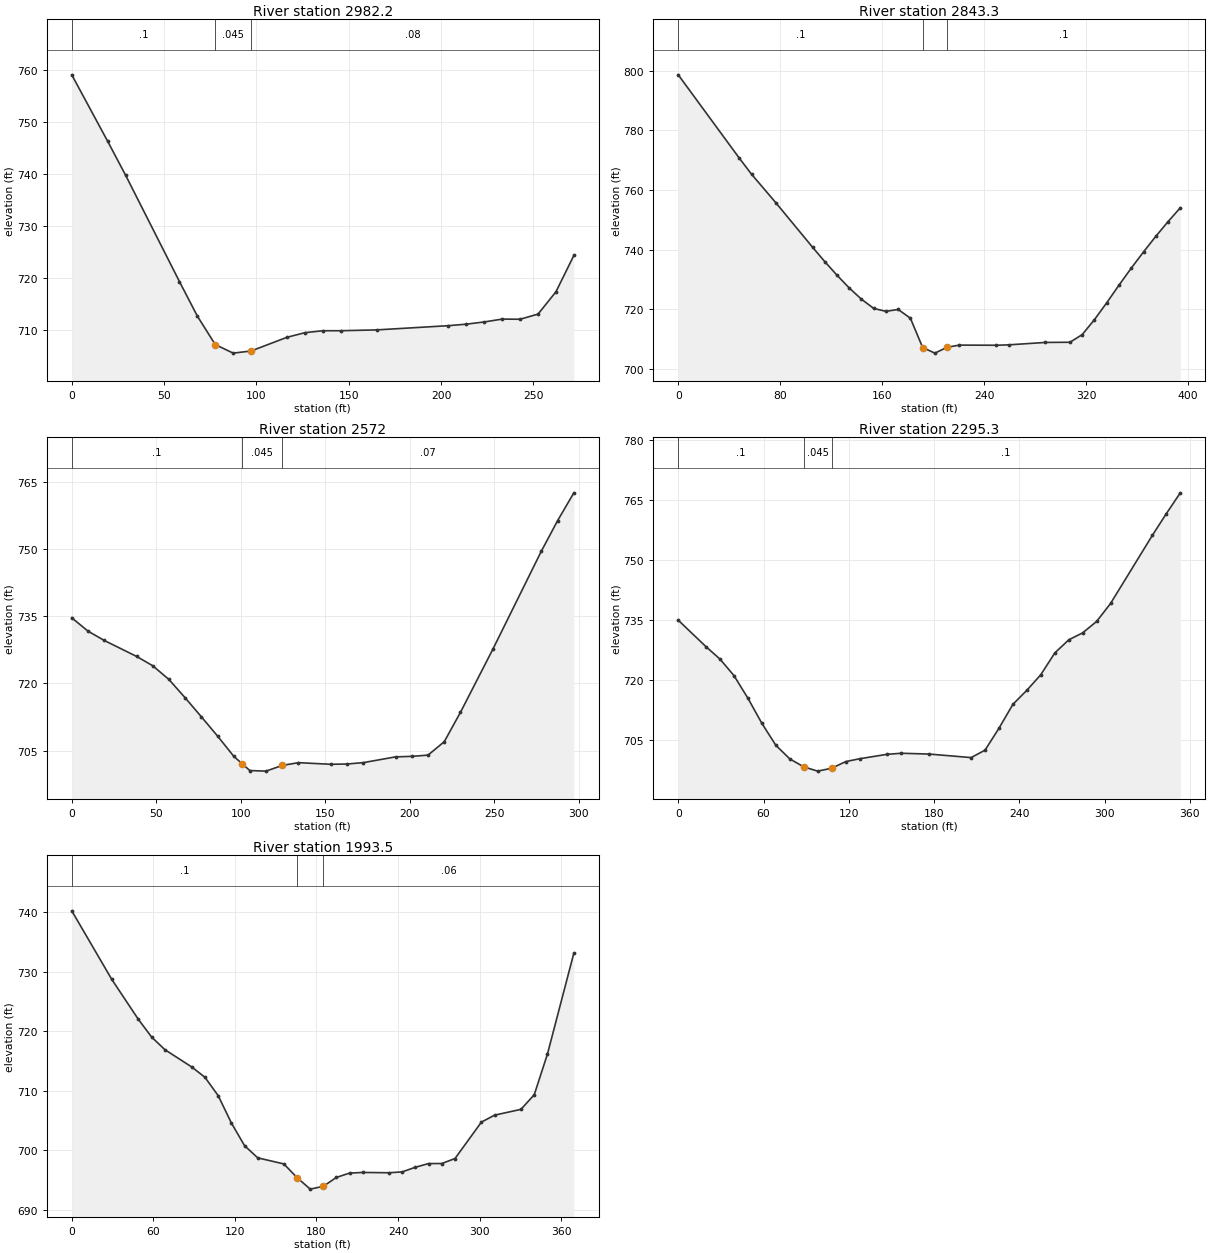
Type RM Length L Ch R = 1 ,2982.2  ,142.4,138.9,133
XS GIS Cut Line= 2
     1785663.558      471488.637     1785855.889      471680.852
#Sta/Elev= 21
       0  759.08    19.4  746.32    29.1   739.8    58.3  719.31      68  712.66
    77.7  707.18    87.4  705.53    97.1  705.94   116.5  708.57   126.2  709.46
     136  709.84   145.7  709.84   165.1     710   203.9  710.81   213.6   711.1
   223.4  711.53   233.1  712.08   242.8  712.05   252.5  713.04   262.2  717.33
   271.9  724.32
#Mann= 3 , 0 , 0
       0      .1       0    77.7    .045       0    97.1     .08       0
Bank Sta=77.7,97.1
XS Rating Curve= 0 ,0
Exp/Cntr=0.3,0.1

Type RM Length L Ch R = 1 ,2843.3  ,269.9,271.3,275.1
XS GIS Cut Line= 3
     1785528.546       471534.45     1785642.941      471663.635
     1785827.145       471786.61
#Sta/Elev= 30
       0  798.56    47.9  770.67    57.5  765.29    76.7  755.67   105.4  740.83
     115  736.01   124.6  731.45   134.2  727.17   143.8  723.42   153.4  720.33
     163  719.35   172.6  719.99   182.2  717.04   191.8  707.24   201.4  705.36
   211.1  707.34   220.7  708.05   249.6     708   259.2  708.13   288.1  708.94
   307.4     709     317  711.56   326.6  716.56   336.3  722.25   345.9  728.13
   355.5  733.82   365.2   739.3   374.8  744.49   384.4  749.41     394  754.03
#Mann= 3 , 0 , 0
       0      .1       0   191.8    .045       0   211.1      .1       0
Bank Sta=191.8,211.1
XS Rating Curve= 0 ,0
Exp/Cntr=0.3,0.1

Type RM Length L Ch R = 1 ,2572    ,287.7,276.7,265.8
XS GIS Cut Line= 2
     1785422.699      471824.804     1785647.018      472019.748
#Sta/Elev= 27
       0  734.66     9.6  731.68    19.2   729.6    38.4  726.02    47.9  723.95
    57.5  720.88    67.1  716.79    76.7  712.54    86.3  708.23    95.9   703.7
   100.9  702.03   105.4  700.52     115  700.39   124.6  701.67   134.2  702.28
   153.4  701.92     163  701.98   172.6  702.29   191.7  703.58   201.3  703.69
   210.9  703.97   220.5  706.97   230.1  713.55   249.3  727.67     278  749.58
   287.6  756.38   297.2  762.59
#Mann= 3 , 0 , 0
       0      .1       0   100.9    .045       0   124.6     .07       0
Bank Sta=100.9,124.6
XS Rating Curve= 0 ,0
Exp/Cntr=0.3,0.1

Type RM Length L Ch R = 1 ,2295.3  ,314.5,301.7,287.3
XS GIS Cut Line= 2
     1785255.895      472083.124     1785586.971       472206.34
#Sta/Elev= 30
       0  734.94    19.6  728.31    29.4  725.22    39.2  721.12    49.1  715.42
    58.9  709.16    68.7  703.71    78.5  700.31    88.3  698.33    98.1  697.26
   107.9  697.97   117.8  699.63   127.6  700.35   147.2  701.47     157  701.72
   176.6  701.52   206.1  700.64   215.9   702.5   225.7  707.97   235.5  713.94
   245.3  717.44   255.1  721.32     265  726.77   274.8  730.04   284.6  731.79
   294.4  734.63   304.2  739.11   333.6  756.11   343.4  761.51   353.3  766.74
#Mann= 3 , 0 , 0
       0      .1       0    88.3    .045       0   107.9      .1       0
Bank Sta=88.3,107.9
XS Rating Curve= 0 ,0
Exp/Cntr=0.3,0.1

Type RM Length L Ch R = 1 ,1993.5  ,107.9,81.8,62.8
XS GIS Cut Line= 4
     1785101.463      472319.902       1785206.5      472372.451
     1785312.446      472365.908     1785450.819      472411.551
#Sta/Elev= 30
       0  740.23    29.4  728.73    48.9  722.04    58.7  719.05    68.5  716.92
    88.1  714.04    97.9   712.3   107.7   709.2   117.4  704.62   127.1   700.8
   136.8  698.76     156  697.74   165.7  695.45   175.4  693.51     185  693.98
   194.6  695.47   204.3   696.2     214  696.31   233.3  696.26     243   696.4
   252.7  697.18   262.4   697.8   272.2  697.81   281.9  698.65   301.3  704.76
     311  705.93   330.4   706.9   340.2  709.37   349.9   716.2   369.3  733.13
#Mann= 3 , 0 , 0
       0      .1       0   165.7    .045       0     185     .06       0
Bank Sta=165.7,185
XS Rating Curve= 0 ,0
Exp/Cntr=0.3,0.1