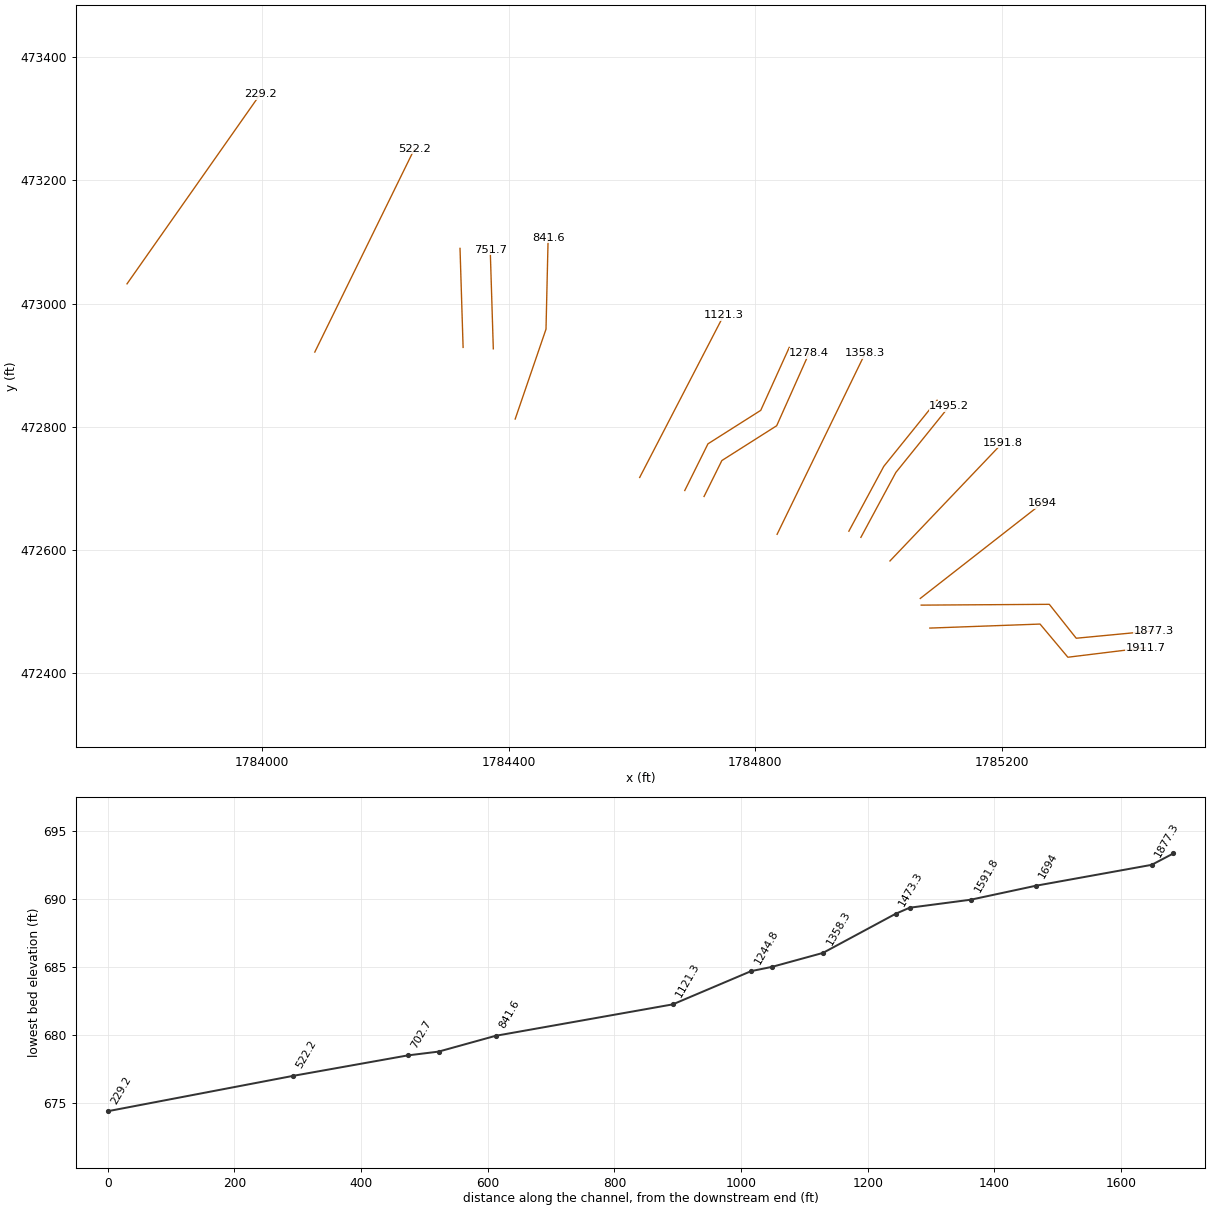
HEC-RAS study CANEFORK1.prj: CANEFORK1

--- CANEFORK1.g02 (geometry) --- (continued)

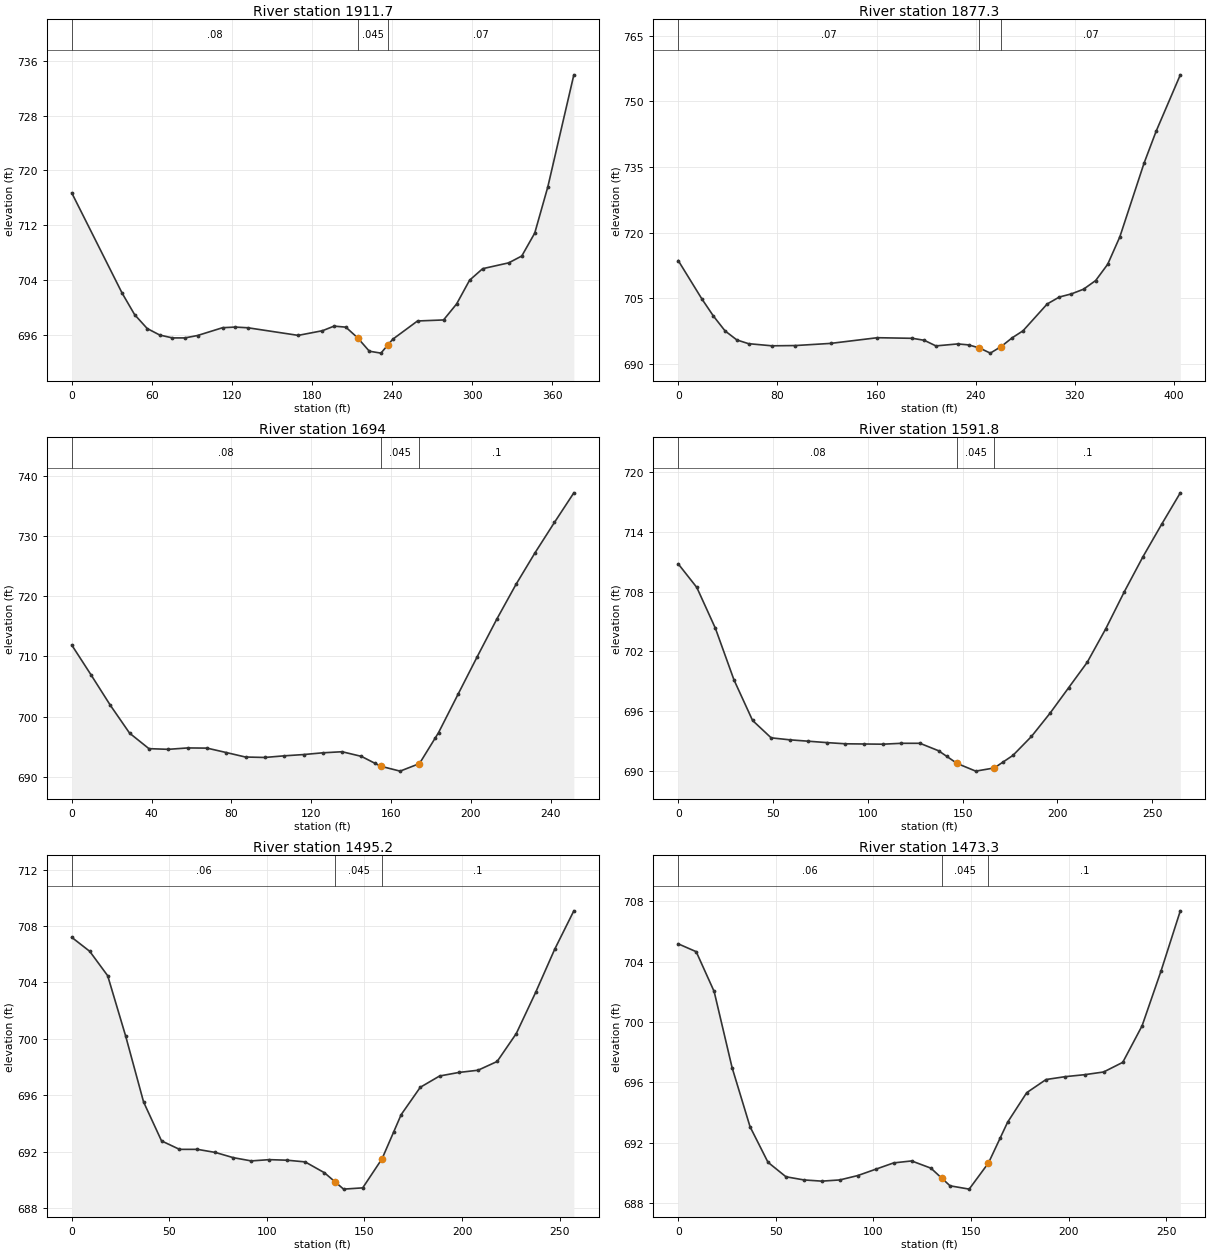
Type RM Length L Ch R = 1 ,1911.7  ,48.4,34.4,32.2
XS GIS Cut Line= 4
     1785083.463      472473.496     1785262.317      472480.001
     1785307.456      472426.182     1785433.416      472441.638
#Sta/Elev= 30
       0  716.71    37.7   702.1    47.1  698.95    56.5  696.93    65.9  695.98
    75.4  695.56    84.8  695.56    94.2  695.91     113  697.05   122.4  697.14
   131.9  697.04   169.6  695.93   187.8  696.61   196.5  697.28   205.3  697.13
   214.1  695.58   222.9  693.62   231.6  693.34   236.9  694.56   240.4  695.36
     259  698.03   278.5  698.18   288.3  700.52     298  703.98   307.8  705.66
   327.3  706.51   337.1  707.51   346.8  710.85   356.6  717.59   376.1  733.94
#Mann= 3 , 0 , 0
       0     .08       0   214.1    .045       0   236.9     .07       0
Bank Sta=214.1,236.9
XS Rating Curve= 0 ,0
Exp/Cntr=0.3,0.1

Type RM Length L Ch R = 1 ,1877.3  ,119.7,183.3,226.7
XS GIS Cut Line= 4
     1785069.406      472510.738     1785277.335      472512.046
     1785320.987      472457.013     1785447.323      472469.022
#Sta/Elev= 30
       0  713.63    18.9  704.95    28.4  700.96    37.8  697.57    47.3  695.51
    56.7  694.66    75.6  694.17    94.5  694.23   122.9  694.72   160.7  696.02
     189  695.88   198.5  695.43   207.9  694.15   225.5   694.6   234.3  694.38
     243  693.68   251.8   692.5   260.6  694.01   269.4  695.99   278.2   697.6
   297.7  703.72   307.5  705.31   317.2  706.02     327  707.09   336.8  709.07
   346.5  712.78   356.3  719.04   375.8  735.83   385.6  743.16   405.1  756.03
#Mann= 3 , 0 , 0
       0     .07       0     243    .045       0   260.6     .07       0
Bank Sta=243,260.6
XS Rating Curve= 0 ,0
Exp/Cntr=0.3,0.1

Type RM Length L Ch R = 1 ,1694    ,97.7,102.2,106.5
XS GIS Cut Line= 2
     1785067.934      472521.597     1785266.307      472676.528
#Sta/Elev= 29
       0  711.89     9.7  706.92    19.4  701.86      29  697.26    38.7  694.69
    48.4  694.58    58.1  694.81    67.8  694.78    77.4  694.05    87.1   693.3
    96.8  693.23   106.5   693.5   116.2  693.71   125.8     694   135.5  694.18
   145.2  693.41   152.1  692.24   154.9  691.77   164.6  690.96   174.3  692.21
   182.1   696.4   183.9  697.37   193.6  703.69   203.3  709.98     213  716.15
   222.7  721.96   232.3  727.24     242  732.26   251.7  737.16
#Mann= 3 , 0 , 0
       0     .08       0   154.9    .045       0   174.3      .1       0
Bank Sta=154.9,174.3
XS Rating Curve= 0 ,0
Exp/Cntr=0.3,0.1

Type RM Length L Ch R = 1 ,1591.8  ,94.1,96.6,99.2
XS GIS Cut Line= 2
     1785018.765       472582.44     1785201.404      472774.106
#Sta/Elev= 30
       0  710.79     9.8  708.42    19.6  704.31    29.4  699.12    39.2  695.04
      49  693.29    58.8  693.09    68.6  692.95    78.4  692.81    88.2  692.69
    98.1  692.67   107.9  692.65   117.7  692.74   127.5  692.74   137.3  691.99
   141.5  691.44   147.1  690.71   156.9  689.94   166.7  690.26   171.5  690.88
   176.5  691.52   186.3  693.43   196.1  695.77   205.9  698.33   215.7  700.89
   225.5  704.27   235.3     708   245.1  711.51     255  714.79   264.8  717.94
#Mann= 3 , 0 , 0
       0     .08       0   147.1    .045       0   166.7      .1       0
Bank Sta=147.1,166.7
XS Rating Curve= 0 ,0
Exp/Cntr=0.3,0.1

Type RM Length L Ch R = 1 ,1495.2  ,21.9,21.9,21.8
XS GIS Cut Line= 3
     1784971.564       472620.73     1785028.309      472726.048
     1785114.755      472833.227
#Sta/Elev= 30
       0   707.2     9.2  706.21    18.4  704.48    27.6  700.21    36.8  695.53
      46  692.77    55.2  692.17    64.4  692.17    73.6  691.95    82.8  691.58
      92  691.35   101.2  691.44   110.4   691.4   119.6  691.28   129.5  690.51
   134.9  689.87   139.3  689.35   149.1  689.44     159   691.5   164.9  693.38
   168.8  694.63   178.6  696.57   188.5  697.37   198.3  697.62   208.2  697.78
     218   698.4   227.8  700.38   237.7  703.29   247.5  706.36   257.3  709.08
#Mann= 3 , 0 , 0
       0     .06       0   134.9    .045       0     159      .1       0
Bank Sta=134.9,159
XS Rating Curve= 0 ,0
Exp/Cntr=0.3,0.1

Type RM Length L Ch R = 1 ,1473.3  ,107.9,115,121.5
XS GIS Cut Line= 3
     1784952.043      472630.717     1785008.788      472736.035
     1785095.234      472843.214
#Sta/Elev= 30
       0  705.18     9.2  704.66    18.4  702.02    27.6  696.97    36.8  693.05
      46  690.69    55.2  689.73    64.4  689.52    73.6  689.44    82.8  689.52
      92  689.81   101.2  690.23   110.4  690.65   119.6  690.78   129.5   690.3
   135.1  689.63   139.3  689.13   149.1  688.91     159  690.65   165.1  692.33
   168.8  693.35   178.6  695.31   188.5  696.18   198.3  696.37   208.2   696.5
     218  696.68   227.8  697.32   237.7  699.74   247.5  703.41   257.3  707.37
#Mann= 3 , 0 , 0
       0     .06       0   135.1    .045       0     159      .1       0
Bank Sta=135.1,159
XS Rating Curve= 0 ,0
Exp/Cntr=0.3,0.1

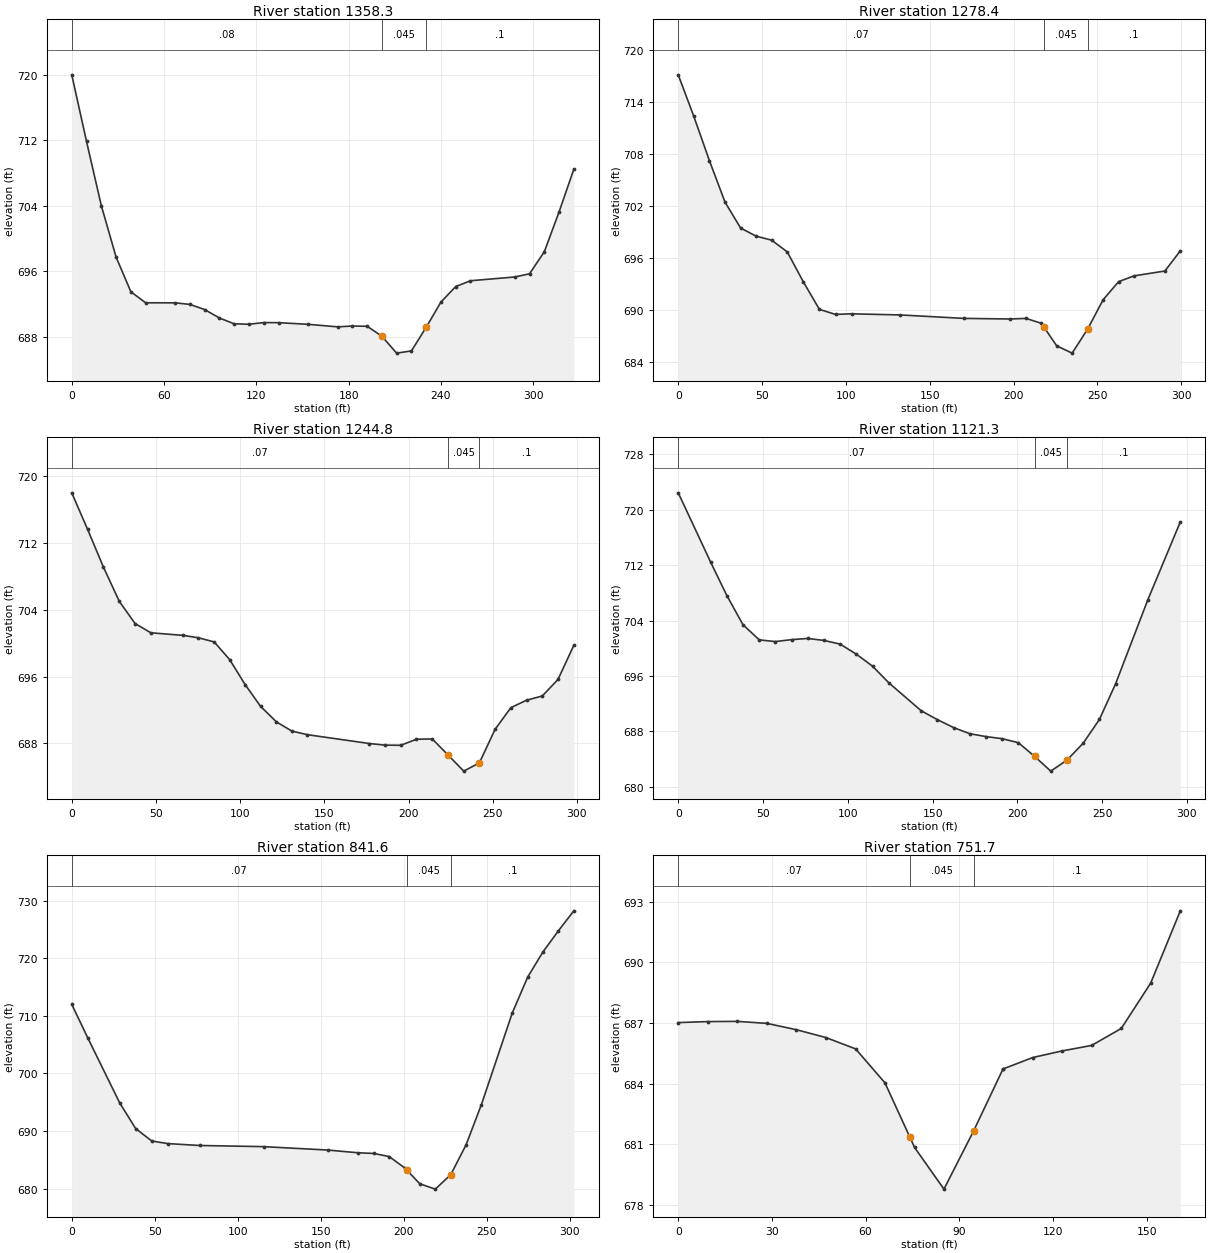
Type RM Length L Ch R = 1 ,1358.3  ,79.1,80,81.1
XS GIS Cut Line= 2
     1784835.606      472625.683     1784978.403      472919.243
#Sta/Elev= 30
       0  720.02     9.6  711.88    19.2  704.05    28.8  697.77    38.4  693.53
      48  692.18    67.2  692.17    76.8  691.98    86.4  691.35      96  690.32
   105.6  689.61   115.2  689.56   124.8  689.76   134.4  689.75   153.6  689.55
   172.8  689.24   182.4  689.34     192  689.31   201.5  688.11   211.2  686.03
   220.8   686.3   230.4  689.18     240  692.27   249.6  694.16   259.2  694.87
     288  695.33   297.6  695.72   307.2  698.41   316.8  703.28   326.4   708.5
#Mann= 3 , 0 , 0
       0     .08       0   201.5    .045       0   230.4      .1       0
Bank Sta=201.5,230.4
XS Rating Curve= 0 ,0
Exp/Cntr=0.3,0.1

Type RM Length L Ch R = 1 ,1278.4  ,33.7,33.5,33.4
XS GIS Cut Line= 4
      1784717.06      472687.102     1784745.954      472745.359
     1784834.922      472801.859     1784887.512      472919.668
#Sta/Elev= 26
       0  717.14     9.3  712.34    18.6  707.23    27.9  702.44    37.2  699.45
    46.4  698.52    55.7  698.05      65   696.7    74.6  693.24    84.2  690.06
    93.8  689.48   103.4  689.55   132.1  689.42   170.4  689.02   198.1  688.95
   207.3  689.02   216.5  688.46   218.2  687.98   225.7  685.85   234.9  685.01
   244.1  687.78   253.4  691.18   262.6  693.26   271.8  693.93   290.2  694.49
   299.4  696.82
#Mann= 3 , 0 , 0
       0     .07       0   218.2    .045       0   244.1      .1       0
Bank Sta=218.2,244.1
XS Rating Curve= 0 ,0
Exp/Cntr=0.3,0.1

Type RM Length L Ch R = 1 ,1244.8  ,125.3,123.6,122
XS GIS Cut Line= 4
     1784685.763      472696.732     1784723.396      472772.486
     1784809.046      472826.827      1784855.35      472928.968
#Sta/Elev= 29
       0  717.97     9.4   713.6    18.8  709.09    28.2     705    37.6  702.34
      47  701.23    65.8  700.93    75.2  700.64    84.6  700.14    93.8  698.02
     103  695.03   112.2  692.42   121.5  690.59   130.7  689.48   139.9  689.05
   176.8  687.99     186   687.8   195.4  687.78   204.7   688.5   214.1  688.54
   223.4  686.64   232.8  684.69   242.1  685.68   251.4  689.68   260.8  692.28
   270.1  693.17   279.5  693.68   288.8  695.66   298.2  699.74
#Mann= 3 , 0 , 0
       0     .07       0   223.4    .045       0   242.1      .1       0
Bank Sta=223.4,242.1
XS Rating Curve= 0 ,0
Exp/Cntr=0.3,0.1

Type RM Length L Ch R = 1 ,1121.3  ,266,279.7,293.3
XS GIS Cut Line= 2
     1784612.574      472717.918      1784748.84      472980.819
#Sta/Elev= 28
       0  722.46    19.1  712.45    28.7   707.6    38.2   703.4    47.8  701.21
    57.3  700.97    66.9  701.25    76.4  701.42      86  701.13    95.5   700.6
   105.1  699.14   114.6  697.41   124.2  695.01   143.3  690.97   152.8  689.69
   162.4  688.54   171.9  687.66   181.5  687.24     191  686.94   200.6  686.36
   210.2  684.37   219.7  682.25   229.2  683.83   238.8  686.28   248.4  689.72
   257.9  694.85     277  707.04   296.1  718.26
#Mann= 3 , 0 , 0
       0     .07       0   210.2    .045       0   229.2      .1       0
Bank Sta=210.2,229.2
XS Rating Curve= 0 ,0
Exp/Cntr=0.3,0.1

Type RM Length L Ch R = 1 ,841.6   ,88.2,90,91.5
XS GIS Cut Line= 3
     1784410.566      472812.713     1784460.566      472958.546
     1784464.037       473106.92
#Sta/Elev= 24
       0  711.98     9.6   706.2    28.9  694.89    38.5  690.45    48.2  688.29
    57.8  687.84    77.1  687.51   115.6  687.31   154.2  686.72   172.7  686.24
     182  686.13   191.3  685.59   200.6  683.63   201.8  683.27   209.8  680.86
   219.1  679.94   228.4  682.45   237.6  687.59   246.9  694.61   265.5   710.5
   274.8  716.73     284  721.09   293.3  724.75   302.6  728.21
#Mann= 3 , 0 , 0
       0     .07       0   201.8    .045       0   228.4      .1       0
Bank Sta=201.8,228.4
XS Rating Curve= 0 ,0
Exp/Cntr=0.3,0.1

Type RM Length L Ch R = 1 ,751.7   ,48.9,48.9,48.9
XS GIS Cut Line= 2
     1784375.061      472926.698     1784370.068        473087.4
#Sta/Elev= 20
       0  687.02     9.5  687.07    18.9  687.08    28.4  686.98    37.8  686.67
    47.3  686.28    56.8  685.72    66.2  684.04    74.1  681.38    75.7  680.84
    85.1  678.78    94.6  681.66     104  684.72   104.1  684.73   113.5  685.29
     123  685.62   132.4  685.89   141.9  686.73   151.3  688.97   160.8  692.55
#Mann= 3 , 0 , 0
       0     .07       0    74.1    .045       0    94.6      .1       0
Bank Sta=74.1,94.6
XS Rating Curve= 0 ,0
Exp/Cntr=0.3,0.1

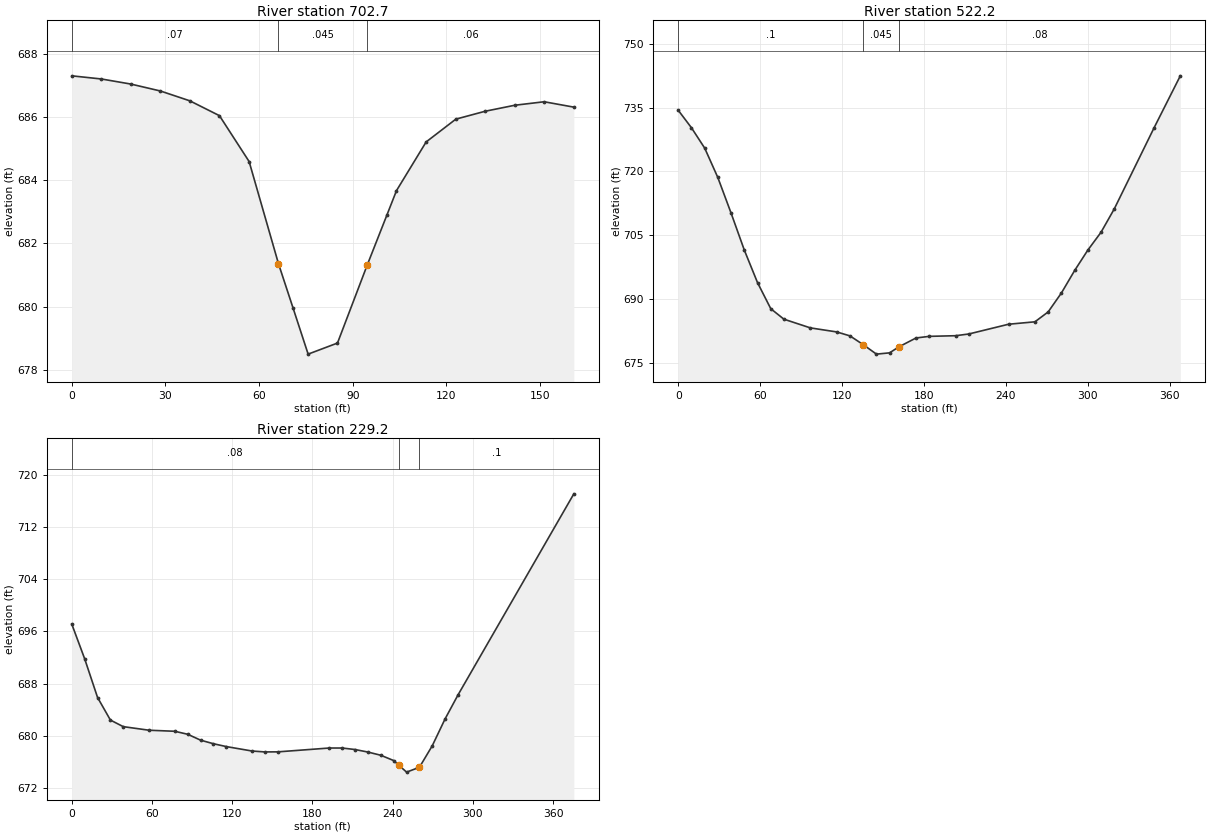
Type RM Length L Ch R = 1 ,702.7   ,195.2,180.6,165.9
XS GIS Cut Line= 2
     1784326.034      472928.968      1784321.04      473089.669
#Sta/Elev= 20
       0   687.3     9.5   687.2    18.9  687.04    28.4  686.82    37.8  686.51
    47.3  686.04    56.8  684.59    66.2  681.36    70.9  679.95    75.7   678.5
    85.1  678.85    94.6  681.31   100.9  682.89     104  683.67   113.5  685.21
     123  685.93   132.4  686.18   141.9  686.37   151.3  686.48   160.8  686.31
#Mann= 3 , 0 , 0
       0     .07       0    66.2    .045       0    94.6     .06       0
Bank Sta=66.2,94.6
XS Rating Curve= 0 ,0
Exp/Cntr=0.3,0.1

Type RM Length L Ch R = 1 ,522.2   ,297.7,293,288.2
XS GIS Cut Line= 2
     1784085.369      472921.396     1784247.305      473251.598
#Sta/Elev= 30
       0  734.35     9.7  730.23    19.4  725.44      29  718.54    38.7  710.18
    48.4  701.47    58.1   693.8    67.8  687.68    77.4  685.22    96.8  683.17
   116.1  682.22   125.8  681.29   135.5  679.23   145.2     677   154.8   677.3
   161.7  678.72   174.2   680.8   183.9  681.18   203.2  681.33   212.9  681.74
     242  684.03   261.3   684.6     271  686.93   280.7  691.38   290.4  696.67
     300  701.44   309.7  705.65   319.4  711.14   348.4  730.11   367.8  742.45
#Mann= 3 , 0 , 0
       0      .1       0   135.5    .045       0   161.7     .08       0
Bank Sta=135.5,161.7
XS Rating Curve= 0 ,0
Exp/Cntr=0.3,0.1

Type RM Length L Ch R = 1 ,229.2   ,238.1,229.2,220.2
XS GIS Cut Line= 2
     1783780.647      473032.141     1783996.525       473339.42
#Sta/Elev= 27
       0  697.12     9.6  691.82    19.3  685.85    28.9  682.39    38.5  681.38
    57.8  680.83      77  680.67    86.7  680.21    96.3  679.31   105.9  678.76
   115.6  678.32   134.8  677.64   144.4   677.5   154.1  677.51   192.6   678.1
   202.2   678.1   211.8  677.87   221.5  677.48   231.1  676.99   240.7  676.18
   244.6  675.46   250.4   674.4     260  675.14   269.6  678.44   279.2  682.57
   288.9  686.26   375.5  717.11
#Mann= 3 , 0 , 0
       0     .08       0   244.6    .045       0     260      .1       0
Bank Sta=244.6,260
XS Rating Curve= 0 ,0
Exp/Cntr=0.3,0.1